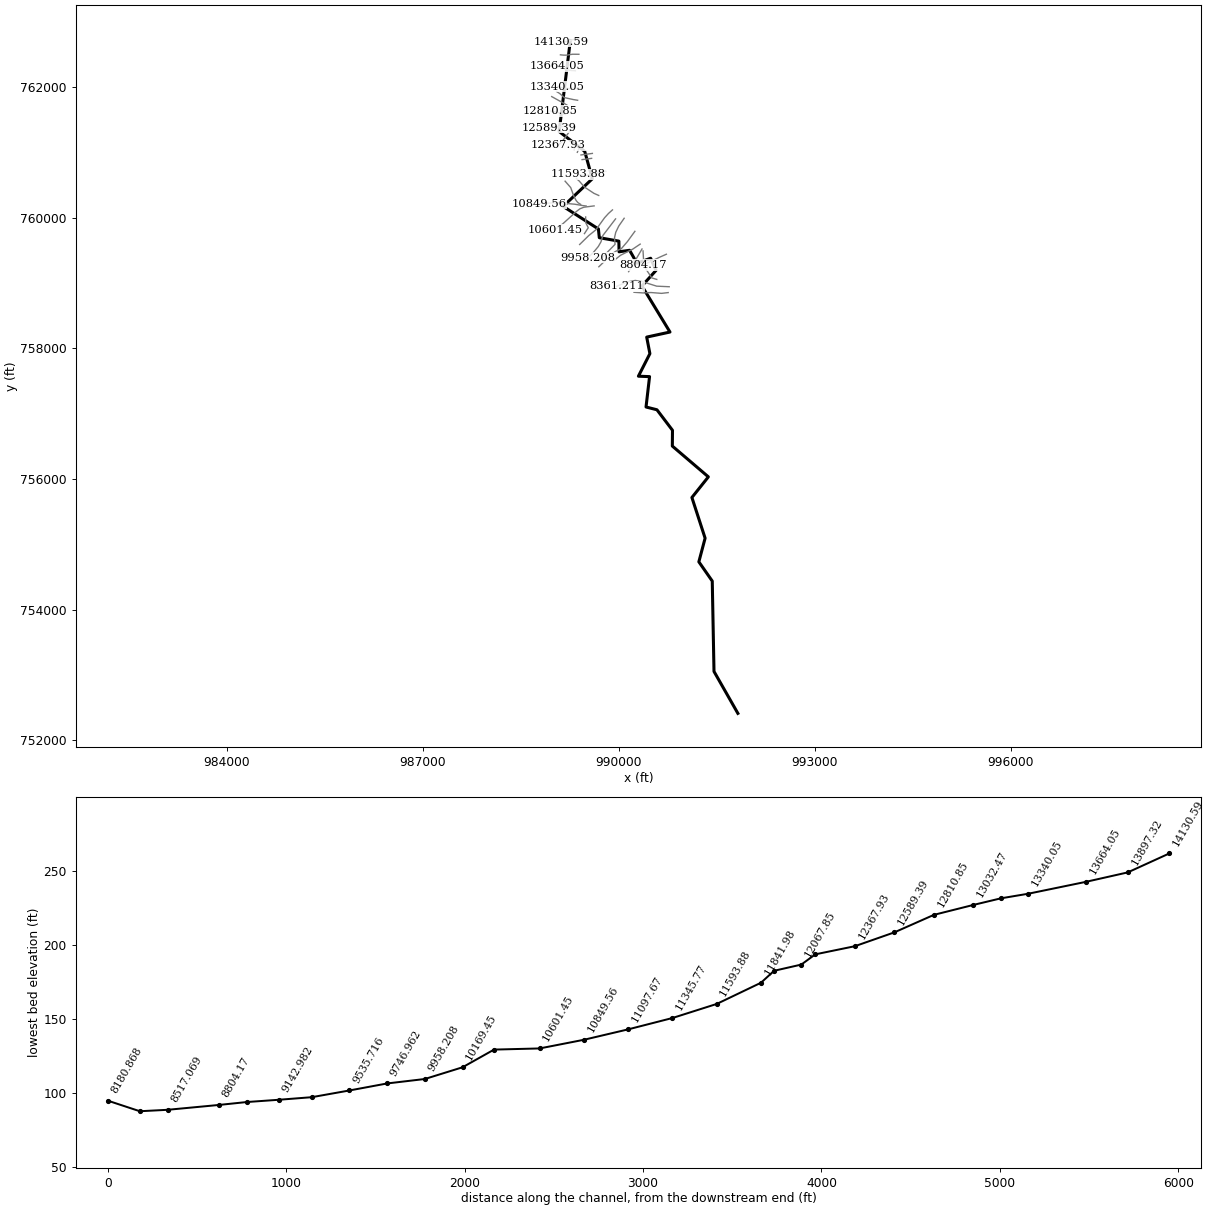
--- 67_ras.prj (project) ---

Proj Title=67
Current Plan=p01
Default Exp/Contr=0.3,0.1
English Units
Geom File=g01
Flow File=f01
Plan File=p01
Y Axis Title=Elevation
X Axis Title(PF)=Main Channel Distance
X Axis Title(XS)=Station
BEGIN DESCRIPTION:
RFD model 67 exported to HEC-RAS
END DESCRIPTION:

--- 67_ras.p01 (plan) ---

Plan Title=Plan 01
Program Version=4.10
Short Identifier=Plan 01
Geom File=g01
Flow File=f01
Subcritical Flow
Calc Critical at every XS
Secant Critical Depth

--- 67_ras.f01 (steady flow) ---

Flow Title=Flow 01
Program Version=5.01
Number of Profiles= 6
Profile Names=10yr,25yr,50yr,100yr,100plus,500yr
River Rch & RM=67,50,14130.59
   89.33  168.89  254.11  347.52  507.39 1147.15
River Rch & RM=67,50,13897.32
   92.93  175.73  264.46  361.73  528.12 1187.58
River Rch & RM=67,50,13664.05
   97.77  184.94  278.37   380.8  555.97 1241.43
River Rch & RM=67,50,13340.05
  116.73  221.08  333.09  455.92  665.65  1450.6
River Rch & RM=67,50,13186.26
  122.68  232.43  350.29  479.56  700.16 1515.54
River Rch & RM=67,50,12810.85
  126.21  239.17  360.52  493.62  720.69 1553.99
River Rch & RM=67,50,12589.39
  128.95  244.41  368.45  504.52   736.6 1583.63
River Rch & RM=67,50,12367.93
  129.92  246.26  371.27  508.39  742.25 1594.16
River Rch & RM=67,50,12146.47
  133.79  253.65  382.49  523.82  764.78 1636.03
River Rch & RM=67,50,12067.85
  135.71  257.33  388.07   531.5  775.99  1656.8
River Rch & RM=67,50,11915.39
  136.29  258.43  389.74   533.8  779.35 1663.02
River Rch & RM=67,50,11593.88
  151.24  287.05   433.2  593.61  866.66 1823.52
River Rch & RM=67,50,11345.77
  153.43  291.27  439.64   602.5  879.64  1847.4
River Rch & RM=67,50,11097.67
  155.06  294.42  444.44  609.13  889.33 1865.24
River Rch & RM=67,50,10849.56
  280.11   533.2  806.65 1106.73 1615.82 3120.03
River Rch & RM=67,50,10601.45
  281.86  536.59  811.83 1113.91  1626.3 3137.79
River Rch & RM=67,50,10346.19
  284.55  541.81  819.82 1124.98 1642.47 3165.16
River Rch & RM=67,50,10169.45
  285.19  543.04   821.7 1127.58 1646.27 3171.58
River Rch & RM=67,50,9958.208
  287.24  547.02   827.8 1136.03  1658.6 3192.43
River Rch & RM=67,50,9746.962
  306.88  584.97  885.82 1216.26 1775.75 3388.71
River Rch & RM=67,50,9535.716
  307.66  586.48  888.13 1219.47 1780.42 3396.53
River Rch & RM=67,50,9324.469
  307.82  586.78  888.59 1220.11 1781.36  3398.1
River Rch & RM=67,50,9142.982
   312.6  596.07  902.83 1239.85 1810.18 3446.42
River Rch & RM=67,50,8961.168
  314.11  599.01  907.36 1246.15 1819.38 3461.94
River Rch & RM=67,50, 8804.17
  314.41  599.59  908.26 1247.41 1821.21 3465.05
River Rch & RM=67,50,8517.069
  329.82   629.7  954.62 1311.92  1915.4  3623.4
River Rch & RM=67,50,8361.211
  330.55  631.14  956.84 1315.02 1919.93 3631.02
River Rch & RM=67,50,8180.868
  331.73  633.45   960.4 1319.98 1927.16 3643.19
River Rch & RM=67,50,8037.211
  349.99  668.92 1014.82 1395.47 2037.39 3825.44
River Rch & RM=67,50,7832.822
  350.56  670.05 1016.57 1397.91 2040.94  3831.4
River Rch & RM=67,50,7628.432
  352.99  674.82 1023.96 1408.24 2056.03 3856.72
River Rch & RM=67,50,7424.043
   354.7  678.19 1029.17 1415.52 2066.67 3874.55
River Rch & RM=67,50,7061.587
  356.12  680.99 1033.51 1421.59 2075.52 3889.38
River Rch & RM=67,50,6771.846
  371.83   711.7 1080.82 1487.45 2171.68  4048.2
River Rch & RM=67,50,6571.956
  372.97  713.94 1084.27 1492.27 2178.72 4059.87
River Rch & RM=67,50,6396.007
  373.97  715.89 1087.29 1496.49 2184.88 4070.07
River Rch & RM=67,50,6133.012
   374.8  717.54 1089.84 1500.07  2190.1  4078.8
River Rch & RM=67,50,5996.464
  377.15  722.19 1097.06 1510.19 2204.87  4103.5
River Rch & RM=67,50,5797.199
  377.98  723.83 1099.61 1513.76 2210.08 4112.21
River Rch & RM=67,50,5556.358
  378.39  724.64 1100.88 1515.53 2212.68 4116.56
River Rch & RM=67,50,5216.189
  385.38   738.5 1122.41 1545.74 2256.77 4190.23
River Rch & RM=67,50,5064.175
  385.79  739.31 1123.67 1547.51 2259.36 4194.54
River Rch & RM=67,50,4913.114
  387.83  743.36 1129.97 1556.35 2272.27 4216.11
River Rch & RM=67,50,4764.347
   388.1   743.9 1130.81 1557.53 2273.99 4218.98
Boundary for River Rch & Prof#=67,50,1
Up Type= 0
Dn Type= 2
Boundary for River Rch & Prof#=67,50,2
Up Type= 0
Dn Type= 2
Boundary for River Rch & Prof#=67,50,2
Up Type= 0
Dn Type= 2
Boundary for River Rch & Prof#=67,50,2
Up Type= 0
Dn Type= 2
Boundary for River Rch & Prof#=67,50,2
Up Type= 0
Dn Type= 2
Boundary for River Rch & Prof#=67,50,2
Up Type= 0
Dn Type= 2

--- 67_ras.g01 (geometry) ---

Geom Title=67
Program Version=4.10

River Reach=67,50
Reach XY= 30
989261.311374815762713.490028123989090.255676735761320.439482827
989481.248898479761016.972030669989597.973508392760596.860953462
989151.186868817760174.166378174989691.128976005759828.173196287
989704.822090254 759694.80938926 990004.14934297759642.233842987
990007.084591049759479.049637775990168.760872679759501.905514416
990280.902139249759304.301757479990490.436911553759380.411688268
990572.963199348759194.498436888 990357.61678787758956.073163373
990786.673548358758250.848745055990430.157714267758173.216920389
990479.144565643757919.831843914990303.363315615757574.779760575
990474.009772081 757568.30532407990420.082413915757103.329389552
990586.853706989757061.069576531990824.939675452756747.128678372
990822.665831194756505.264286719 991374.11119658756034.158613083
991122.219548837755718.095898051 991324.37309793755095.472816136
991228.432255644754733.582334729991433.706034199754439.042887209
991460.362294931753055.555890377991825.855608747752413.915311435

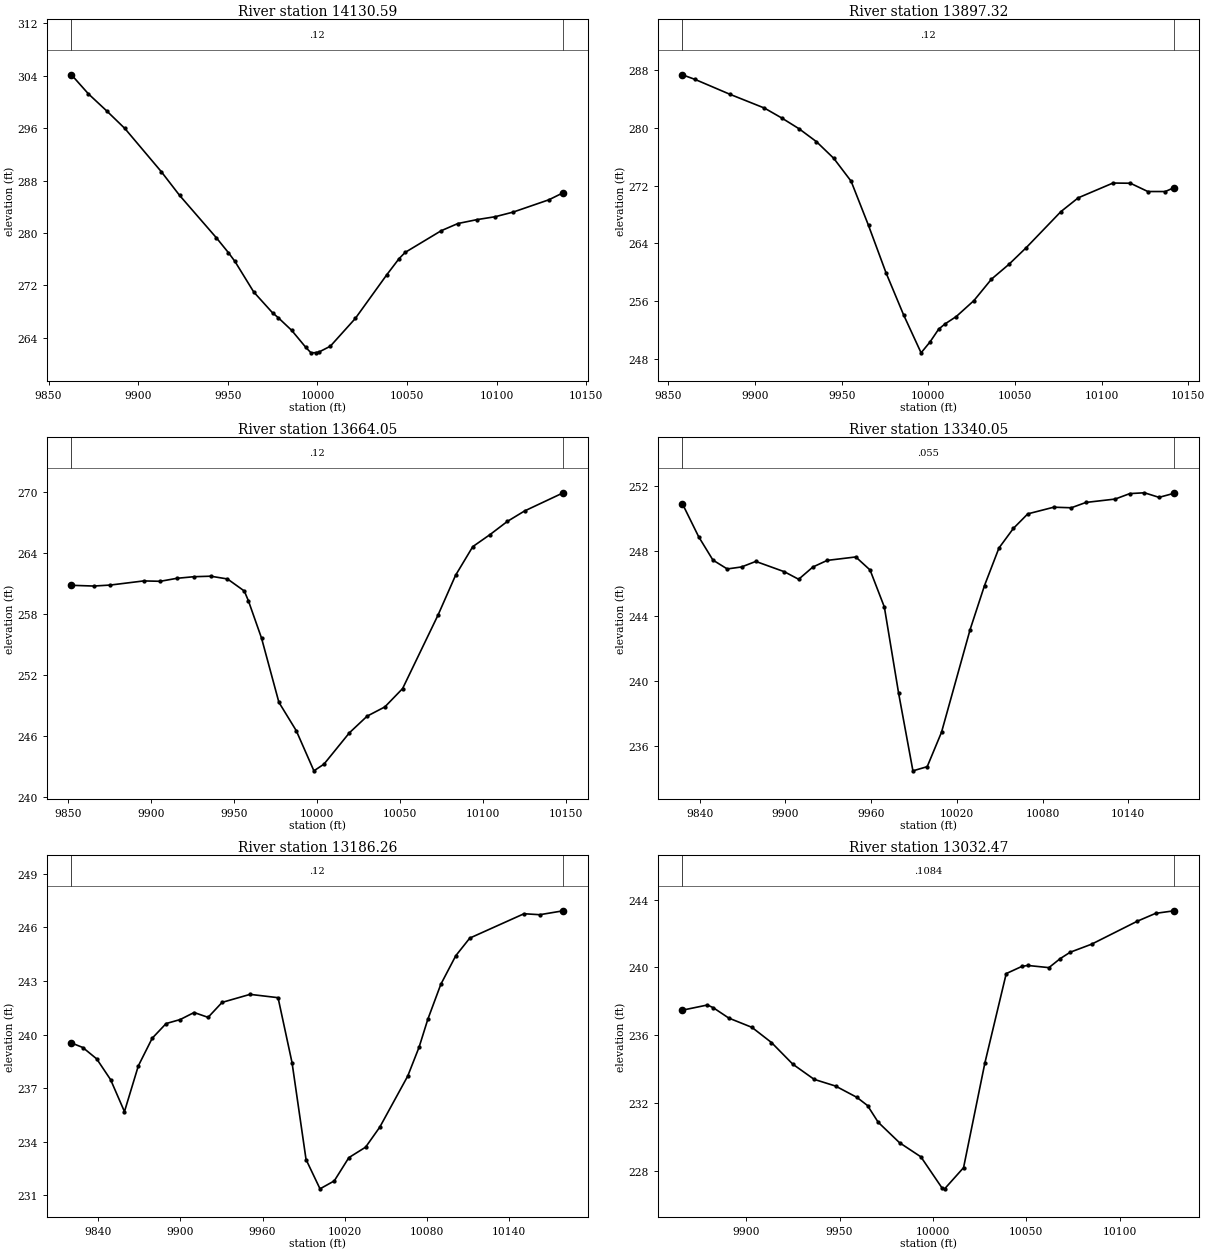
Type RM Length L Ch R = 1 ,14130.59,233.273500,233.273500,233.273500
XS GIS Cut Line= 6
989394.358141937762746.257114555989308.471746296  762729.1477464
989243.183650129762705.320697906989218.386228836762698.744979995
989176.402883734762693.926819016989127.011186033762693.115443789
#Sta/Elev= 29
9862.745304.15719872.243301.23379882.394298.64749892.544295.95939912.845 289.377
9923.099 285.7419943.648279.25989950.356276.99469953.998 275.655 9964.49 270.985
9974.981267.81019978.207267.0542 9985.67265.12939993.569262.52349996.445261.7018
    9999261.7292   10001261.842510007.22262.713910021.15266.948410038.71273.6185
10045.55276.076110048.96 277.03310069.09 280.347 10078.4281.445610089.22282.0496
10099.22282.485610109.22283.190110129.22285.074110137.21 286.153
#Mann= 3 , 0 , 0
9862.745    0.12       09862.745    0.12       010137.21    0.12       0
#XS Ineff= 2 , 0
       0                               0
Bank Sta=9862.745,10137.21
Exp/Cntr=0.3,0.1

Type RM Length L Ch R = 1 ,13897.32,233.273500,233.273500,233.273500
XS GIS Cut Line= 6
989392.342239473762502.039265905 989295.92676442762503.006034003
989216.969170051762490.609913328 989191.56222055762488.544465585
989157.311252289762489.117864005989109.866188707 762493.76217692
#Sta/Elev= 28
9858.076 287.3239865.421286.68079885.429284.63649905.438282.72229915.442281.3488
9925.446279.85749935.449278.07969945.451275.7734 9955.46272.61489965.522266.4878
9975.584259.96859985.708254.16119995.854248.8846   10001250.3885   10006252.1601
10009.71252.886710016.17253.907410026.33 256.10510036.46259.069710046.49261.1077
10056.53263.424210076.54 268.40910086.54270.3149 10106.6272.357910116.65272.3291
 10126.7271.184910136.75 271.182 10141.9271.7236
#Mann= 3 , 0 , 0
9858.076    0.12       09858.076    0.12       0 10141.9    0.12       0
#XS Ineff= 2 , 0
       0                               0
Bank Sta=9858.076,10141.9
Exp/Cntr=0.3,0.1

Type RM Length L Ch R = 1 ,13664.05,324.000000,324.000000,324.000000
XS GIS Cut Line= 6
 989338.44418188 762250.20228705989278.248656071762253.256576758
989232.567591957762260.807216689989202.267448415762270.107253665
989120.478545041762300.837667268989052.573195406762320.070328281
#Sta/Elev= 27
9851.912260.81669865.373260.74369875.386260.84239895.412261.24839905.425261.2117
9915.477261.50749925.613261.66249935.749261.71399945.884261.4419 9956.02260.2546
9958.486259.29299966.402255.61229976.862 249.2869987.322246.49039997.944242.5358
10003.99243.192810019.32246.2838   10030247.924410040.68248.835510051.36250.6414
10072.72257.891110083.25261.799610093.64264.629510104.03 265.81510114.43267.1098
10124.82268.141510148.13269.9335
#Mann= 3 , 0 , 0
9851.912    0.12       09851.912    0.12       010148.13    0.12       0
#XS Ineff= 2 , 0
       0                               0
Bank Sta=9851.912,10148.13
Exp/Cntr=0.3,0.1

Type RM Length L Ch R = 1 ,13340.05,153.789800,153.789800,153.789800
XS GIS Cut Line= 6
989406.425440982 761979.24149279989246.954549041761978.907459203
989235.252351846761979.231950495989202.846203998761980.813444801
989147.021245743761988.841834109989064.644291711762006.780681816
#Sta/Elev= 30
9827.822250.92769839.248248.89059849.248 247.4539859.248246.90879869.248247.0308
9879.248247.37159899.248246.73759909.248 246.2739919.248  247.039929.248 247.435
9949.248247.64649959.248246.84329969.248244.56699979.248239.25899989.249234.4886
9999.253234.744610009.27236.862410029.29243.180410039.37245.887710049.47248.1948
10059.58249.402710069.68250.297510087.84250.707110100.15250.672310110.38251.0003
10130.85251.208310141.08 251.54410151.32251.594510161.55 251.31310172.15 251.565
#Mann= 3 , 0 , 0
9827.822   0.055       09827.822   0.055       010172.15   0.055       0
#XS Ineff= 2 , 0
       0                               0
Bank Sta=9827.822,10172.15
Exp/Cntr=0.3,0.1

Type RM Length L Ch R = 1 ,13186.26,153.789800,153.789800,153.789800
XS GIS Cut Line= 6
989373.192018393761798.260138635989305.230985532761809.516331825
989177.757927855761837.613337564989156.021986778761851.067405584
989099.932927218761900.988839971989050.112818043761932.277369428
#Sta/Elev= 30
 9820.41 239.5339828.713239.2777 9838.85238.64149848.986237.48049859.122235.6904
9869.258238.25219879.394239.79889889.533240.61829899.751240.84039909.969241.2365
9920.188240.96499930.406241.80249950.843242.2517 9971.28 242.0669981.498238.4267
9991.716233.010910001.91231.369510012.32231.813810022.97233.115610035.21233.7022
10045.54234.820810065.97237.679610074.27239.300410080.64240.858410090.13242.8147
10101.05244.414210111.29245.400710150.87246.763110162.39246.708910179.54246.9288
#Mann= 3 , 0 , 0
 9820.41    0.12       0 9820.41    0.12       010179.54    0.12       0
#XS Ineff= 2 , 0
       0                               0
Bank Sta=9820.41,10179.54
Exp/Cntr=0.3,0.1

Type RM Length L Ch R = 1 ,13032.47,221.613500,221.613500,221.613500
XS GIS Cut Line= 2
989206.774868846761726.950288296988976.306118816761854.554454952
#Sta/Elev= 28
9865.794237.47579879.254237.78249882.413237.61769890.684237.00929903.058236.4624
9913.545235.56569924.975234.28599936.406233.39139947.836232.99739959.267232.3306
9964.992231.84469970.697230.85959982.128229.65069993.558228.817510004.99226.9629
10006.28226.927510016.42228.176310027.85234.363510039.28 239.63610047.57240.0557
10050.71240.117210062.14239.988210068.22240.522510073.57240.8984   10085 241.372
10109.51242.729810119.29243.192610129.23243.3446
#Mann= 3 , 0 , 0
9865.794  0.1084       09865.794  0.1084       010129.23  0.1084       0
#XS Ineff= 2 , 0
       0                               0
Bank Sta=9865.794,10129.23
Exp/Cntr=0.3,0.1

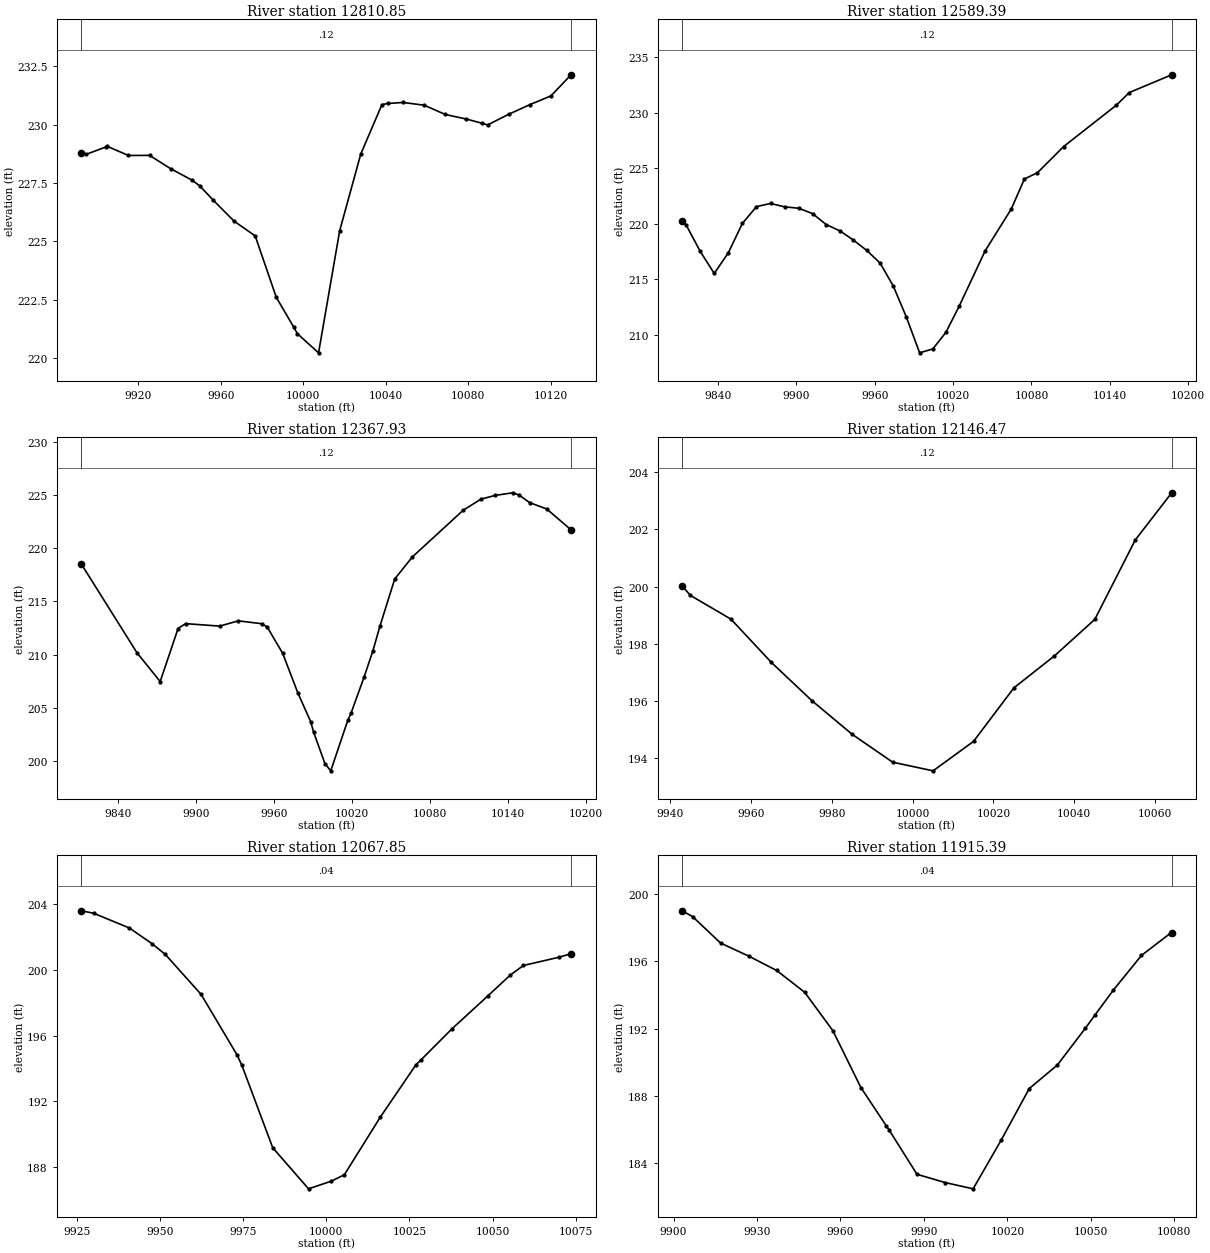
Type RM Length L Ch R = 1 ,12810.85,221.461000,221.461000,221.461000
XS GIS Cut Line= 2
989187.243618846761582.419038281988955.472785473761634.502371654
#Sta/Elev= 30
9892.419228.78589894.718228.72469904.191229.03739904.968229.06719915.217228.6747
9925.467228.68049935.716228.10739945.965 227.622  9949.8227.37299956.215226.7718
9966.464225.86049976.713225.22719986.963222.5893 9995.41221.31679997.212221.0304
10007.46220.213110017.71225.450410027.96228.743610038.21230.856210041.02230.9057
10048.46230.947910058.71230.831310068.96230.432710079.21230.237610086.63230.0607
10089.46229.984510099.71230.441910109.96230.8548 10120.2231.229710129.97232.1358
#Mann= 3 , 0 , 0
9892.419    0.12       09892.419    0.12       010129.97    0.12       0
#XS Ineff= 2 , 0
       0                               0
Bank Sta=9892.419,10129.97
Exp/Cntr=0.3,0.1

Type RM Length L Ch R = 1 ,12589.39,221.461100,221.461100,221.461100
XS GIS Cut Line= 6
989297.823741548761445.453175724 989210.82563952761410.675579063
989159.418779217761396.542212994989109.743725013761390.302393771
989015.307428829761390.397477649988932.843735493761380.626906647
#Sta/Elev= 30
 9812.64 220.2869815.681219.91919826.451217.5378 9837.22215.54119847.989217.4001
9858.759220.04639869.528221.55949880.298221.84519891.067221.54039901.836221.4149
9912.445220.93419922.939219.94359933.432219.37349943.732218.54739953.979217.6094
9964.154 216.4769974.239214.41259984.324211.59469994.409208.390310004.55208.7449
10014.56210.243610024.57212.566310044.57217.581810064.58221.351810074.59224.0487
 10084.6224.618810104.61226.970510144.89230.691110154.96231.840210187.34233.4367
#Mann= 3 , 0 , 0
 9812.64    0.12       0 9812.64    0.12       010187.34    0.12       0
#XS Ineff= 2 , 0
       0                               0
Bank Sta=9812.64,10187.34
Exp/Cntr=0.3,0.1

Type RM Length L Ch R = 1 ,12367.93,221.461000,221.461000,221.461000
XS GIS Cut Line= 6
989322.308359114761386.181662865989287.995778924 761360.71771421
989255.916710878761330.358741156989145.175940467761179.095021246
989112.881529338761144.781546108989070.700614703761109.055915829
#Sta/Elev= 30
9811.513218.50549854.242210.17079872.134207.45399885.903212.45159891.656212.9103
9917.935212.67679932.282213.17389950.602212.89779954.595212.57999966.409210.1236
9978.222206.35829988.017203.68179990.319202.6671    9999199.727810003.46199.0449
10016.55203.787310019.07 204.46910029.05207.8454 10035.9210.339310041.48212.7301
10052.74217.121410066.34219.195710105.47 223.592 10119.2224.639710130.14224.9883
10143.56225.235210148.36225.031110156.66224.305610169.77223.708810188.51221.7443
#Mann= 3 , 0 , 0
9811.513    0.12       09811.513    0.12       010188.51    0.12       0
#XS Ineff= 2 , 0
       0                               0
Bank Sta=9811.513,10188.51
Exp/Cntr=0.3,0.1

Type RM Length L Ch R = 1 ,12146.47,78.618000,78.618000,78.618000
XS GIS Cut Line= 2
989324.830424368761157.071816087989320.924174368761035.978066072
#Sta/Elev= 14
9942.965200.02299945.038199.68889955.044198.86119965.049197.34849975.054196.0139
9985.059194.83349995.064193.859710005.07193.557710015.07194.586610025.08196.4608
10035.09197.574610045.09198.8531 10055.1201.629210064.12203.2789
#Mann= 3 , 0 , 0
9942.965    0.12       09942.965    0.12       010064.12    0.12       0
#XS Ineff= 2 , 0
       0                               0
Bank Sta=9942.965,10064.12
Exp/Cntr=0.3,0.1

Type RM Length L Ch R = 1 ,12067.85,152.463800,152.463800,152.463800
XS GIS Cut Line= 2
989422.920702169761138.408621624989368.233202139761001.689871624
#Sta/Elev= 21
9926.343203.61579930.015203.46469940.785202.56139947.671201.58989951.555200.9534
9962.326 198.5119973.096194.83219974.596194.17679983.866189.15089994.637186.6405
10001.52187.112510005.41187.500310016.18 191.00410026.95194.219110028.45194.5099
10037.72196.397910048.49198.406310055.37199.700810059.26200.276210070.03200.7835
10073.59200.9951
#Mann= 3 , 0 , 0
9926.343    0.04       09926.343    0.04       010073.59    0.04       0
#XS Ineff= 2 , 0
       0                               0
Bank Sta=9926.343,10073.59
Exp/Cntr=0.3,0.1

Type RM Length L Ch R = 1 ,11915.39,73.408400,73.408400,73.408400
XS GIS Cut Line= 2
989598.701952159760984.762788281989424.222785473760961.325288281
#Sta/Elev= 22
9903.055199.0176 9906.79198.6751 9916.88197.0959 9926.97196.3189 9937.06 195.461
 9947.15194.15869957.239191.88019967.329 188.4899976.386186.22579977.419185.9768
9987.509183.31899997.599 182.82910007.69182.453310017.78185.354610027.87188.4261
10037.96189.825710048.05 192.021 10051.5192.805810058.14194.297310068.23196.3591
10078.32197.6386 10079.1197.7182
#Mann= 3 , 0 , 0
9903.055    0.04       09903.055    0.04       0 10079.1    0.04       0
#XS Ineff= 2 , 0
       0                               0
Bank Sta=9903.055,10079.1
Exp/Cntr=0.3,0.1

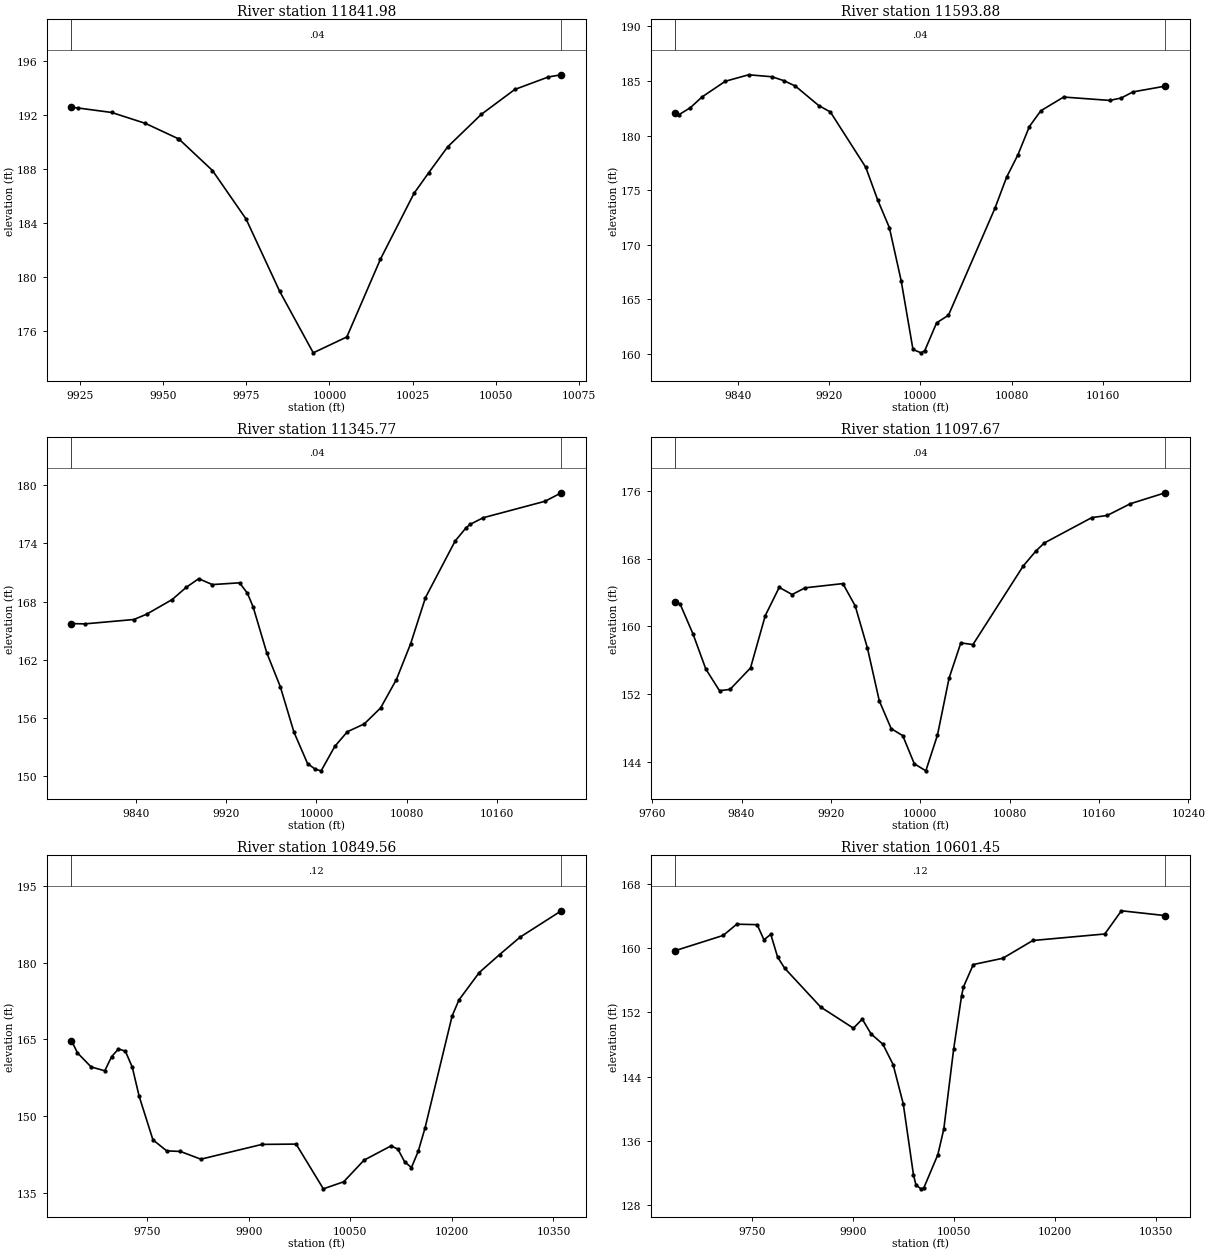
Type RM Length L Ch R = 1 ,11841.98,248.105400,248.105400,248.105400
XS GIS Cut Line= 2
989586.983202189760909.241954952989441.149868846760889.710704967
#Sta/Elev= 19
9922.508192.58029924.508192.52519934.598192.19279944.687191.38819954.464190.2638
9954.776190.22789964.866187.89269974.955184.30089985.044178.94559995.133174.3877
10005.22175.566210015.31 181.327 10025.4186.2055 10029.8 187.72510035.49189.6441
10045.58192.048210055.67 193.89910065.76194.824910069.64194.9861
#Mann= 3 , 0 , 0
9922.508    0.04       09922.508    0.04       010069.64    0.04       0
#XS Ineff= 2 , 0
       0                               0
Bank Sta=9922.508,10069.64
Exp/Cntr=0.3,0.1

Type RM Length L Ch R = 1 ,11593.88,248.105500,248.105500,248.105500
XS GIS Cut Line= 6
989797.877183696760713.497753394989667.678918332760685.888868311
989558.451720117760656.918796462989517.788687132760649.583327016
989449.806304327760649.573388427989377.312731397760662.860813162
#Sta/Elev= 30
9785.348182.10379788.289181.89589798.511182.55119808.734183.53539829.178184.9786
9849.623185.57059870.068185.3872 9880.29185.03589890.513184.53629910.957182.7511
9921.211182.15589952.225177.08079962.563174.10929972.901171.5456 9983.24 166.671
9993.578160.375310000.69160.064210003.93160.2701 10014.3162.818610024.66163.5122
10065.44 173.33610075.56176.158910085.57178.236710095.59180.826110105.61182.2704
10125.63183.528210165.89 183.21910176.06183.438510186.29 183.99910214.59184.5283
#Mann= 3 , 0 , 0
9785.348    0.04       09785.348    0.04       010214.59    0.04       0
#XS Ineff= 2 , 0
       0                               0
Bank Sta=9785.348,10214.59
Exp/Cntr=0.3,0.1

Type RM Length L Ch R = 1 ,11345.77,248.105400,248.105400,248.105400
XS GIS Cut Line= 6
989695.998634823760341.139124598989622.645326316760373.764776021
989488.787471023760462.498864502989462.156039073760487.006119197
989401.077955234760558.435516328 989353.82064755760600.537943825
#Sta/Elev= 30
 9782.71165.73399794.451165.70229838.062166.15429849.268166.69419872.094168.2134
9884.528169.46899895.597170.35769907.663169.75049931.795 169.9329938.807168.8604
9943.861167.45129955.928162.73679967.994159.2267 9980.06154.56019992.126151.3244
    9999150.731510004.19150.569910016.24153.077810027.43154.595810042.47155.4041
10056.96157.049110070.94159.9696 10083.6163.665210096.76 168.41510123.07174.2373
10132.49175.563310136.23175.943710147.87176.631110202.81178.330410217.25179.2043
#Mann= 3 , 0 , 0
 9782.71    0.04       0 9782.71    0.04       010217.25    0.04       0
#XS Ineff= 2 , 0
       0                               0
Bank Sta=9782.71,10217.25
Exp/Cntr=0.3,0.1

Type RM Length L Ch R = 1 ,11097.67,248.105500,248.105500,248.105500
XS GIS Cut Line= 6
989418.806835499760205.064508642989377.620683849  760231.3458709
989350.435779467760263.370415977989314.029286363760332.408923957
989267.190624608760461.898040568989181.318980425760559.934639809
#Sta/Elev= 30
9780.763162.89939785.125 162.6089796.586159.09289808.046 154.9469820.304152.3823
9829.774152.54689848.046155.07319861.277  161.279873.743164.60719885.314163.7617
9896.884164.55369930.732 165.0549941.789  162.419952.733  157.429963.356 151.177
9973.979147.89739984.352147.06759994.661143.7451   10005142.9077 10015.4 147.131
10025.81 153.87310036.32158.041110047.16157.840410092.26167.152710103.65168.9242
   10111169.853710153.58172.860410167.38173.113310188.03174.497710219.27175.7955
#Mann= 3 , 0 , 0
9780.763    0.04       09780.763    0.04       010219.27    0.04       0
#XS Ineff= 2 , 0
       09921.032                       0
Bank Sta=9780.763,10219.27
Exp/Cntr=0.3,0.1

Type RM Length L Ch R = 1 ,10849.56,248.105400,248.105400,248.105400
XS GIS Cut Line= 6
989503.749678876760179.975384685989443.604015293760187.771864969
989331.565835384760206.880663415989120.723805662 760226.66182216
988962.292195352760226.297789229988784.249933371760213.857862777
#Sta/Elev= 30
9638.467164.7744 9647.29162.38839667.457159.64759687.624158.89549697.708161.6468
9707.868163.15669718.041162.71719728.214159.60439738.387153.92199758.733145.4224
9779.039143.27539799.233143.16329829.414141.65539919.764 144.5389970.072144.5973
10010.28135.870410040.32 137.24810070.33141.464510110.33144.254610120.33143.6067
10130.34141.123710140.34140.023110150.34143.201210160.34147.728510200.37169.5897
10210.39172.696110240.43178.059710270.48181.565410300.57184.946210361.55190.1012
#Mann= 3 , 0 , 0
9638.467    0.12       09638.467    0.12       010361.55    0.12       0
#XS Ineff= 2 , 0
       09949.316        10031.34       0
Bank Sta=9638.467,10361.55
Exp/Cntr=0.3,0.1

Type RM Length L Ch R = 1 ,10601.45,255.267800,255.267800,255.267800
XS GIS Cut Line= 6
989625.475009691760181.538225831989469.145672642760161.185583503
 989408.89318007760137.725060789 989354.78989125 760096.50799542
989148.084813525759909.253845975989021.863291358759815.402911962
#Sta/Elev= 30
 9636.57159.67559707.549161.56539727.692162.96489757.942162.90589768.066161.0217
9778.189161.70199788.313158.87799798.575157.50629852.297152.64819900.821150.0215
9913.997151.14669926.932149.31859944.599148.01879959.712145.49519974.825140.5914
9989.938131.77299993.611130.5119   10001130.024910005.08130.096610026.14 134.284
10034.98137.476110049.56147.398910061.32154.043410064.13155.155510078.71 157.941
10122.43158.719610167.15160.933910273.87161.745410298.52 164.63310363.51164.0329
#Mann= 3 , 0 , 0
 9636.57    0.12       0 9636.57    0.12       010363.51    0.12       0
#XS Ineff= 2 , 0
       09944.461                       0
Bank Sta=9636.57,10363.51
Exp/Cntr=0.3,0.1

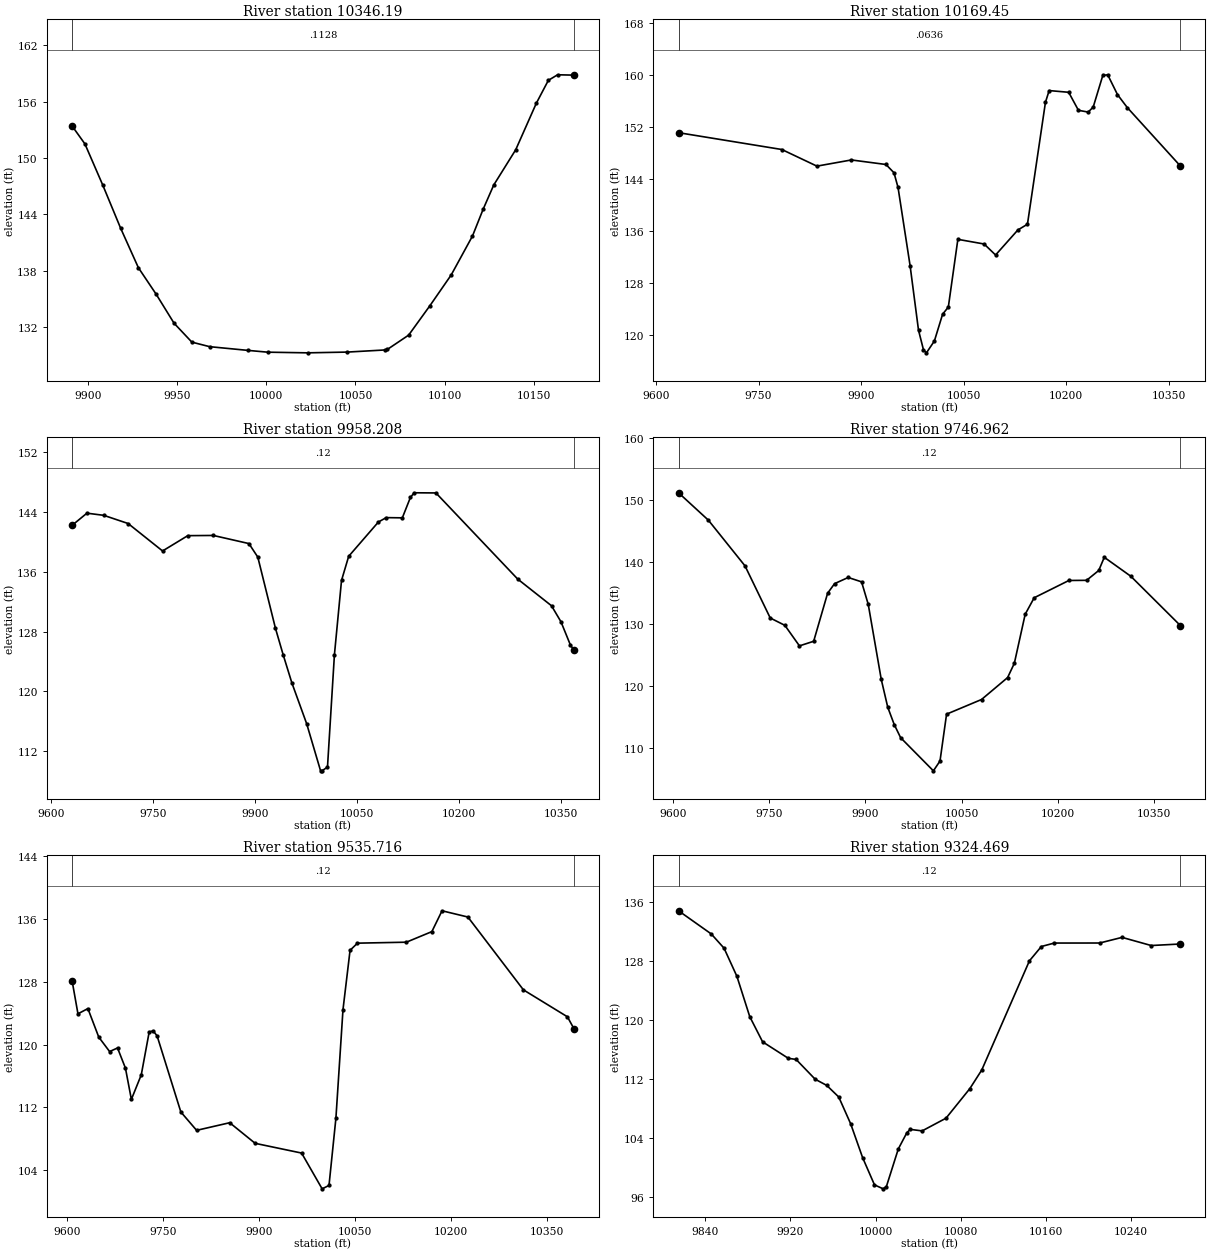
Type RM Length L Ch R = 1 ,10346.19,176.732200,176.732200,176.732200
XS GIS Cut Line= 4
989495.886244535 760012.20970659989495.886244535759927.258159101
989535.634216309759846.982843608989477.181316704759757.355064154
#Sta/Elev= 26
9890.992153.41779898.201151.50669908.201147.12539918.201 142.5429928.201138.3152
9938.201135.48329948.201132.40479958.201 130.3879968.201129.90269989.622129.5085
10000.78129.3164 10023.1129.246610045.42129.327310066.68129.554910067.89129.6112
10079.83131.134110091.76134.2689 10103.7137.544210115.64141.6925 10121.6144.5358
10127.58147.130210139.91150.887910151.46155.839310158.21158.2799 10163.4158.8717
10172.52158.8345
#Mann= 3 , 0 , 0
9890.992  0.1128       09890.992  0.1128       010172.52  0.1128       0
#XS Ineff= 2 , 0
       0                               0
Bank Sta=9890.992,10172.52
Exp/Cntr=0.3,0.1

Type RM Length L Ch R = 1 ,10169.45,211.246200,211.246200,211.246200
XS GIS Cut Line= 6
989906.465456301760120.559310169989845.323332654760065.741036423
989784.809253912759999.084417047989652.650235844759815.509431765
989543.545166889759727.451970629989403.970479869759590.603362909
#Sta/Elev= 30
9632.797151.14029783.981148.55449835.333 145.9989885.761146.94919936.411146.2512
9948.134144.97649954.048142.72529971.685130.71099984.009120.78449991.303117.7539
9995.629117.298910007.25119.121210019.29123.236410027.66124.338610041.61 134.745
10080.05134.0282 10096.8132.338110129.41136.183710143.46137.070610169.81155.8198
10175.23157.6146 10203.8157.349910218.08154.579410232.36154.307210239.71155.0817
10253.72159.933310260.93160.041510275.22156.9963 10289.5155.0089 10367.2146.0286
#Mann= 3 , 0 , 0
9632.797  0.0636       09632.797  0.0636       0 10367.2  0.0636       0
#XS Ineff= 2 , 0
       0                               0
Bank Sta=9632.797,10367.2
Exp/Cntr=0.3,0.1

Type RM Length L Ch R = 1 ,9958.208,211.246200,211.246200,211.246200
XS GIS Cut Line= 6
989953.612977511759982.685517243989759.887178524759728.879278494
989730.673712637759631.751021349989689.733817063759560.327437132
 989620.36054827759476.407527602989531.336964474759386.953467122
#Sta/Elev= 30
9630.578142.21199652.464143.84079677.214143.55249713.102142.45869763.839138.7865
9800.965140.83499838.602140.86189890.989139.77629904.086137.96589930.113128.4349
9941.354124.93179954.295121.13369976.045115.68719996.498109.39899998.579109.3903
10006.69109.8965 10016.9124.907210027.35 134.84710037.89138.074110081.65142.6596
10093.15143.2459 10116.9 143.21710128.77145.937310134.32146.567610166.39146.5458
10286.85135.024910336.57131.460610350.47129.325910364.38126.217810369.48125.5353
#Mann= 3 , 0 , 0
9630.578    0.12       09630.578    0.12       010369.48    0.12       0
#XS Ineff= 2 , 0
       0                               0
Bank Sta=9630.578,10369.48
Exp/Cntr=0.3,0.1

Type RM Length L Ch R = 1 ,9746.962,211.246200,211.246200,211.246200
XS GIS Cut Line= 6
990085.478069887759992.254975328990002.433313749759872.689649705
989956.457716085759777.030282676989938.113320993  759696.7169182
989945.870546995759592.825846797989707.402723116759349.073919772
#Sta/Elev= 30
9608.909151.13879655.406 146.7319712.551  139.379751.847130.98669774.665129.8014
9797.367126.4983 9819.54127.23789841.287134.9703 9852.16136.51549873.364137.5063
9894.207136.80249904.629133.18059924.924121.09229935.032116.62329945.123 113.835
9955.132111.717210006.18106.385410016.48 107.96910026.71115.506610081.22117.8673
10121.87121.396510132.37123.699110149.26131.588610163.29134.242410217.38137.0231
10244.97137.048410263.92138.632410272.56140.753210313.94137.699710391.09129.7774
#Mann= 3 , 0 , 0
9608.909    0.12       09608.909    0.12       010391.09    0.12       0
#XS Ineff= 2 , 0
       0                               0
Bank Sta=9608.909,10391.09
Exp/Cntr=0.3,0.1

Type RM Length L Ch R = 1 ,9535.716,211.246200,211.246200,211.246200
XS GIS Cut Line= 6
990249.551631944759792.439542395990134.036040307759633.751169604
990042.042900329759527.021290584989953.126259039759484.458588716
 989909.44018402 759454.58934756989697.668915438759249.721944903
#Sta/Elev= 30
9607.885128.12349617.087123.90479632.611 124.5689649.602120.94199666.562119.1045
9678.931119.5624  9691.3116.99739700.577113.02239716.038116.14389728.407121.5951
 9734.56121.73639740.776121.10039777.882111.42389802.527109.08739854.254110.0564
9894.031107.43519966.618106.19839998.693101.649810009.44 102.08210020.25110.6462
 10031.3124.439810042.35131.979210053.95132.888110130.34133.010510170.19 134.355
10186.09137.004810226.51136.209910313.27126.950510382.04123.525210392.12122.0259
#Mann= 3 , 0 , 0
9607.885    0.12       09607.885    0.12       010392.12    0.12       0
#XS Ineff= 2 , 0
       09851.631                       0
Bank Sta=9607.885,10392.12
Exp/Cntr=0.3,0.1

Type RM Length L Ch R = 1 ,9324.469,181.487700,181.487700,181.487700
XS GIS Cut Line= 4
990330.472785503759596.741954952990214.587368876759518.616954952
990030.993618816759426.169038281989932.035285503759348.044038281
#Sta/Elev= 30
9814.825134.77159845.545131.63559857.606129.70129869.666125.89149881.726120.4346
9893.786117.02319917.907114.79239925.277114.63399943.166111.95879954.087111.1154
9965.319109.55119976.516105.92429987.712 101.3519998.908 97.6462 10007.197.10902
 10010.197.42273 10021.3102.519210029.33104.7127 10032.5105.163310043.69104.9574
10066.09106.677410088.48110.682310099.67113.201410144.46127.992710155.66129.9315
10167.78130.399710210.44130.405710231.48131.168510258.86130.065110286.22130.2718
#Mann= 3 , 0 , 0
9814.825    0.12       09814.825    0.12       010286.22    0.12       0
#XS Ineff= 2 , 0
       0                               0
Bank Sta=9814.825,10286.22
Exp/Cntr=0.3,0.1

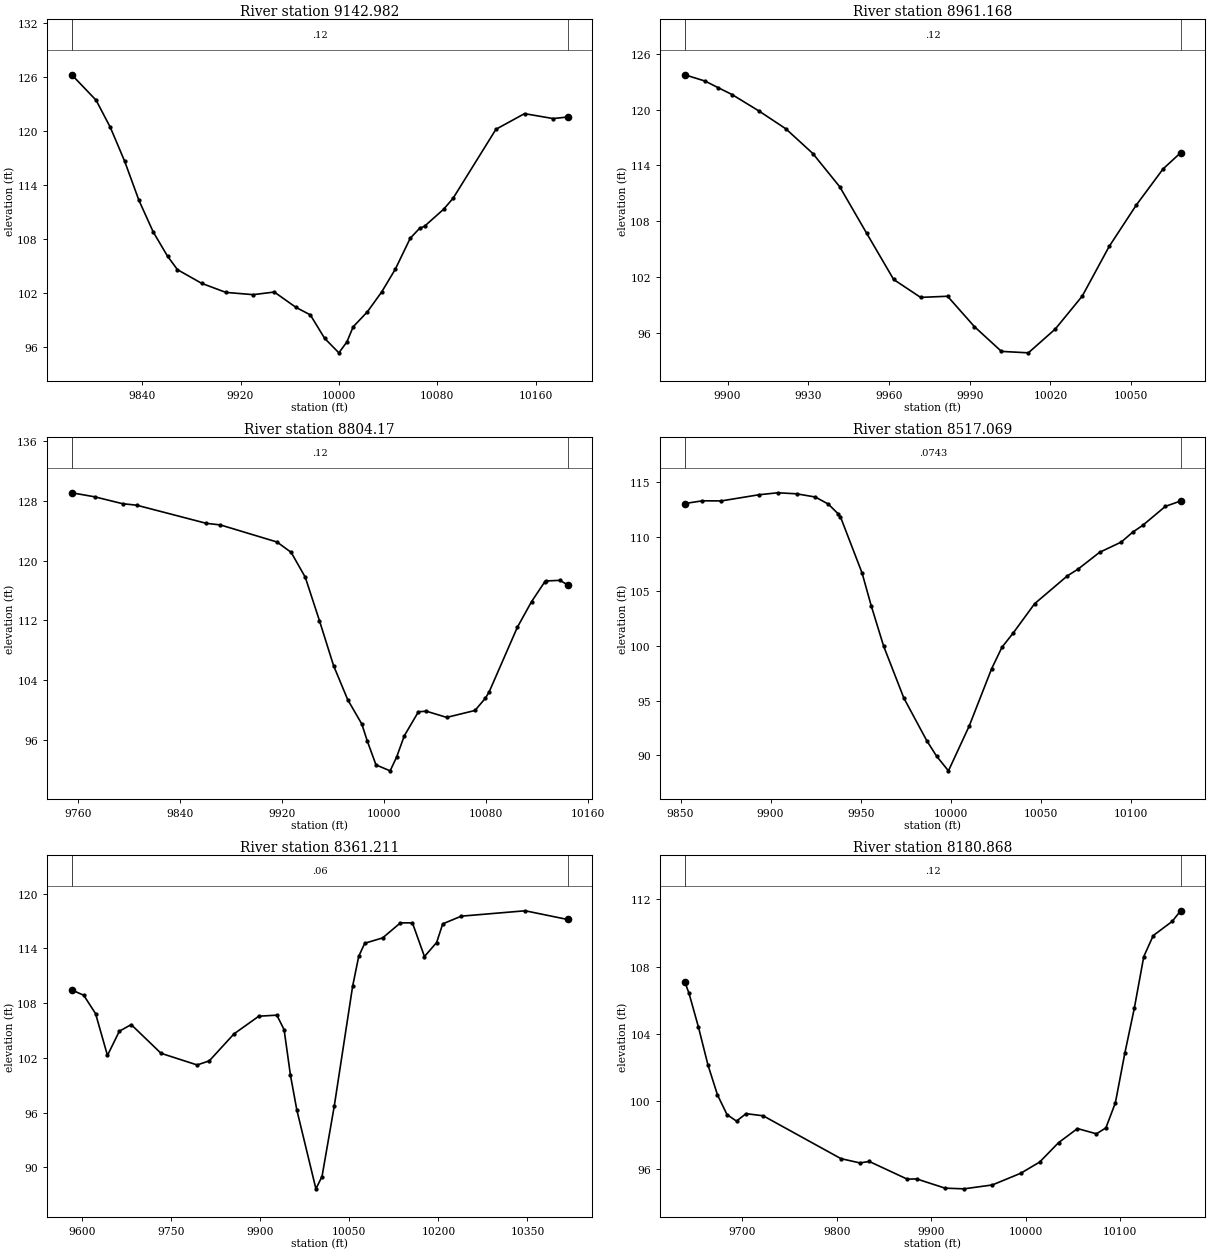
Type RM Length L Ch R = 1 ,9142.982,181.813200,181.813200,181.813200
XS GIS Cut Line= 2
990358.671909988759522.035845101990153.810798854759174.813622862
#Sta/Elev= 30
9782.777126.22289802.556 123.4039814.167120.38179825.778116.63349837.389112.3018
 9849.04108.7857 9860.61106.1181 9868.72104.61679888.399103.10079908.078102.0968
9930.275101.84699947.437102.13689965.107100.43339976.71899.607199988.32997.01244
 9999.9495.3963210006.4796.6051810011.5598.2769810023.1699.9511710034.77  102.15
10045.83104.669610057.99108.105210065.51109.1894 10069.6109.431310085.19111.3251
10092.83112.537310127.66120.180210150.88121.9143 10174.1121.369310185.93121.5406
#Mann= 3 , 0 , 0
9782.777    0.12       09782.777    0.12       010185.93    0.12       0
#XS Ineff= 2 , 0
       0                               0
Bank Sta=9782.777,10185.93
Exp/Cntr=0.3,0.1

Type RM Length L Ch R = 1 ,8961.168,156.998600,156.998600,156.998600
XS GIS Cut Line= 2
990374.296909988 759492.52195619990384.713576645759308.494178399
#Sta/Elev= 21
9884.088123.73889891.622123.06359896.529122.34749901.638121.61769911.654119.8482
 9921.67117.92879931.686115.27619941.702 111.6959951.718106.69149961.734101.7346
 9971.7599.809049981.766 99.93099991.78296.65808 10001.894.0041910011.81 93.8488
10021.8396.4127210031.8599.9527410041.86105.290710051.88109.714310061.89  113.62
10068.41115.3543
#Mann= 3 , 0 , 0
9884.088    0.12       09884.088    0.12       010068.41    0.12       0
#XS Ineff= 2 , 0
       0                               0
Bank Sta=9884.088,10068.41
Exp/Cntr=0.3,0.1

Type RM Length L Ch R = 1 , 8804.17,287.101000,287.101000,287.101000
XS GIS Cut Line= 3
990731.514452159759441.794038281990631.233129829759397.566941783
990379.505243272759277.244178399
#Sta/Elev= 30
9755.178129.06749773.227128.52459795.086127.60289806.015127.40749860.662124.9783
9871.688124.76529916.022122.48149927.106121.0982 9938.19117.76499949.273111.9683
9960.357105.94659971.441101.38639982.52498.119829986.67295.911429993.60892.66246
10004.6991.8682110009.8693.7450910015.78 96.549610026.8699.7724710033.0599.84619
10049.0399.0181610071.1999.9445710079.42101.604610082.28102.422210104.44  111.09
10115.53114.5042 10125.8 117.13310126.61117.2664 10137.7117.353110143.79116.7578
#Mann= 3 , 0 , 0
9755.178    0.12       09755.178    0.12       010143.79    0.12       0
#XS Ineff= 2 , 0
       0                               0
Bank Sta=9755.178,10143.79
Exp/Cntr=0.3,0.1

Type RM Length L Ch R = 1 ,8517.069,155.858000,155.858000,155.858000
XS GIS Cut Line= 3
990584.379035532759056.377371624990508.131775498759079.335030153
990400.338576645 759242.52195619
#Sta/Elev= 30
9852.368113.02299862.163113.27159872.607113.26139893.494113.82369903.937 114.005
 9914.38 113.9129924.824113.61789931.997112.97399937.679112.05219938.786111.8006
9950.771106.67429955.822103.69469962.75599.981469973.96695.243379986.72591.33616
9992.109 89.94199998.70988.5954910010.2592.7006510022.6897.92691 10028.499.88616
10034.66101.193710046.54103.868510064.68106.408710070.62107.0251 10082.6108.5637
10094.59109.498410100.97110.404810106.57111.032910119.11112.762310127.57113.2548
#Mann= 3 , 0 , 0
9852.368  0.0743       09852.368  0.0743       010127.57  0.0743       0
#XS Ineff= 2 , 0
       0                               0
Bank Sta=9852.368,10127.57
Exp/Cntr=0.3,0.1

Type RM Length L Ch R = 1 ,8361.211,180.342500,180.342500,180.342500
XS GIS Cut Line= 6
990775.068446837758944.149233066990582.501562488758952.965197205
990374.206178518759018.996922813 990256.01507032759040.846748209
990129.673757525759016.995084358989969.765028505758949.816874095
#Sta/Elev= 30
9582.295109.44429602.383108.86659622.403106.84639642.419102.26259662.422104.9192
9682.425105.64599732.642102.4984  9793.5101.21779813.974101.66839855.422104.6163
9897.381106.56599927.805106.68159940.033105.08589950.751100.0832 9961.4796.27868
9993.62587.6292410003.91  88.98210024.5496.7097910055.48109.857510065.78113.1442
10075.89114.567410106.04115.156410136.07116.807510156.21116.8036 10176.5113.1107
10196.97114.647210207.29116.6962 10238.6117.541210346.17118.131110417.68117.1769
#Mann= 3 , 0 , 0
9582.295    0.06       09582.295    0.06       010417.68    0.06       0
#XS Ineff= 2 , 0
       0                               0
Bank Sta=9582.295,10417.68
Exp/Cntr=0.3,0.1

Type RM Length L Ch R = 1 ,8180.868,143.657500,143.657500,143.657500
XS GIS Cut Line= 5
990759.405059308 758854.65958856990657.135774165758842.682104722
990494.979069829758855.580933481990374.282886416758849.131519094
990236.081149757758859.266313136
#Sta/Elev= 30
9638.993107.09679643.429106.42949653.497104.40489663.565 102.1559673.634100.3816
9683.70299.21407 9693.7798.824319703.83999.268929722.03599.140269804.29496.59606
9824.35796.340749834.38996.425699874.51595.377319884.54695.389029914.62494.84125
9934.652 94.80019964.695 95.03119994.73895.7258310014.7796.3908110034.8197.54527
10054.8698.3826310074.9198.0697210084.94 98.424110094.97 99.909910104.99 102.862
10115.02 105.52810125.05108.602110135.08109.852210155.13110.692710164.07111.3242
#Mann= 3 , 0 , 0
9638.993    0.12       09638.993    0.12       010164.07    0.12       0
#XS Ineff= 2 , 0
       0                               0
Bank Sta=9638.993,10164.07
Exp/Cntr=0.3,0.1