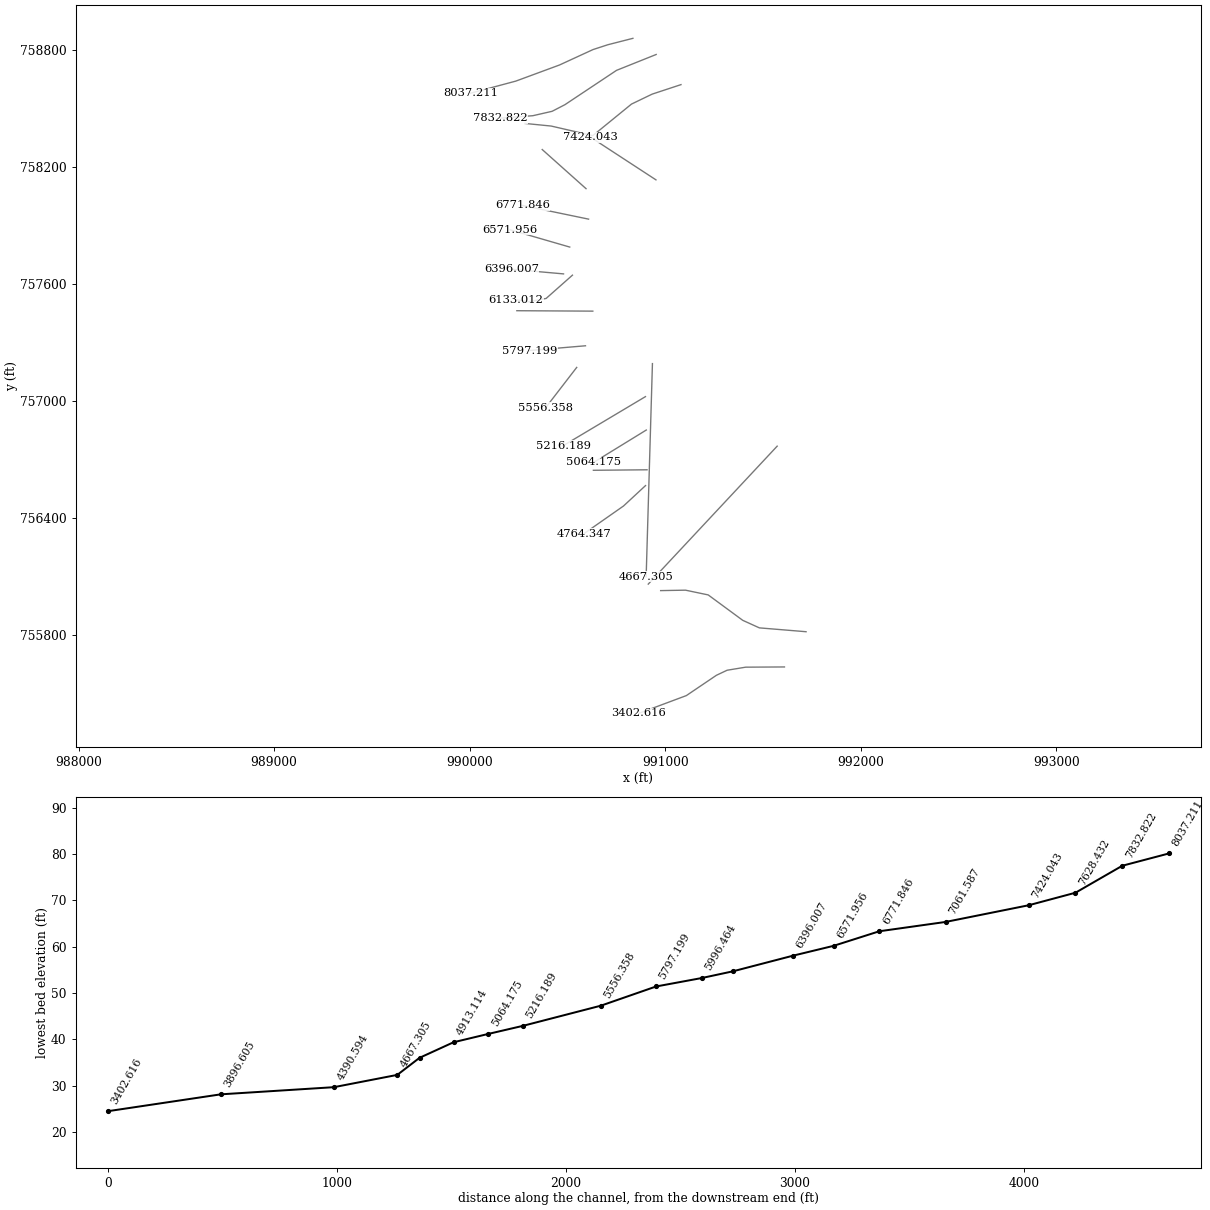
HEC-RAS study 67_ras.prj: 67

--- 67_ras.g01 (geometry) --- (continued)

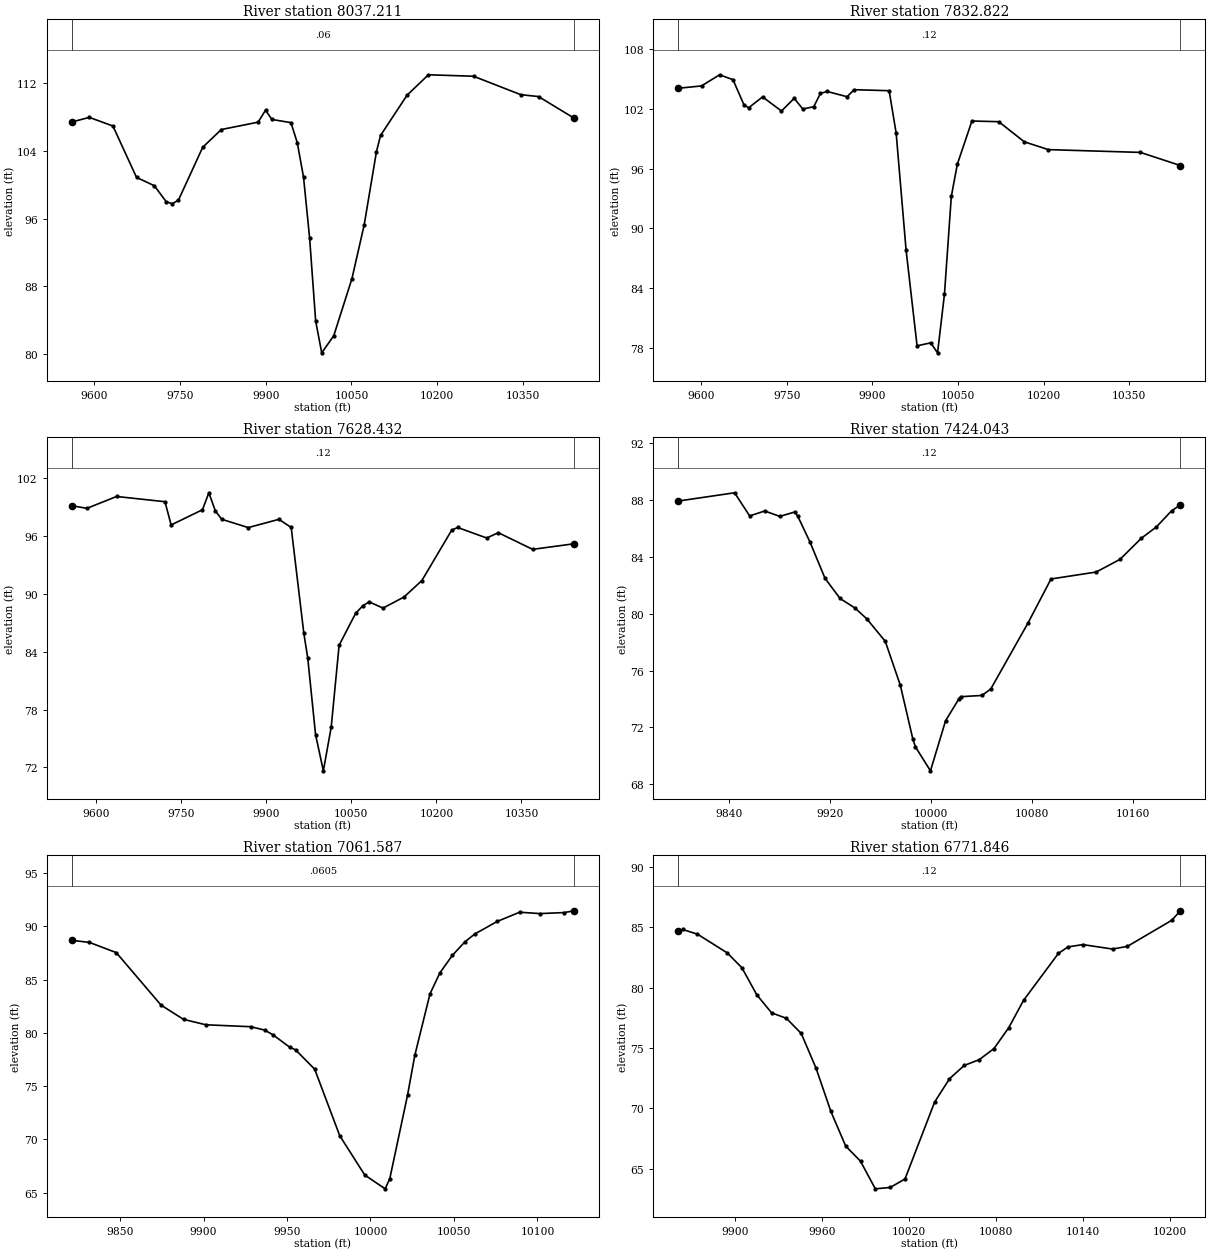
Type RM Length L Ch R = 1 ,8037.211,204.389400,204.389400,204.389400
XS GIS Cut Line= 6
990834.438620824758858.822474375990706.653708736758826.080673364
990630.557693195758801.242754621990458.810113435758721.998215212
990235.691519703758639.462068492 990005.02365542758577.578747118
#Sta/Elev= 30
9560.998107.43369591.388107.9705 9632.68106.95169673.972100.8782 9705.1799.88769
9726.20897.974469736.72897.768569747.24798.175259789.798104.4359 9822.27106.5315
9886.653107.40519899.712108.81879910.829107.72269944.182107.35039955.299104.9573
9966.218100.87959976.816 93.71459987.41383.891259998.01180.1291210019.0682.15039
10050.9188.9096310072.3395.2639210093.75103.9127 10100.9105.831910147.31110.5937
10184.66113.009210263.59112.8362 10346.4 110.65310377.29110.434810439.04107.8985
#Mann= 3 , 0 , 0
9560.998    0.06       09560.998    0.06       010439.04    0.06       0
#XS Ineff= 2 , 0
       0                               0
Bank Sta=9560.998,10439.04
Exp/Cntr=0.3,0.1

Type RM Length L Ch R = 1 ,7832.822,204.389400,204.389400,204.389400
XS GIS Cut Line= 6
990953.360534743758776.005331563990750.673092924758694.624493697
990486.699705571758518.487437259990421.347207434758484.650333467
990323.040156822758462.123810365990155.207923164758449.185854738
#Sta/Elev= 30
9560.325104.08219600.686104.31539632.413105.43689655.876 104.9419675.118102.4048
9683.359102.12019707.671103.21359740.804101.79039763.097103.06699778.217101.9904
9797.366102.22539809.042 103.5569820.718103.75969855.768103.2293 9868.05 103.938
9929.457103.83429941.739 99.58219959.12487.808289978.39178.1740610002.2778.47557
10014.3177.4679910026.3583.3498510038.3993.2007810048.9596.4414910074.51100.7878
10121.57100.716110166.2698.6948810208.3297.9090110369.7297.6286510439.6796.31051
#Mann= 3 , 0 , 0
9560.325    0.12       09560.325    0.12       010439.67    0.12       0
#XS Ineff= 2 , 0
       0                               0
Bank Sta=9560.325,10439.67
Exp/Cntr=0.3,0.1

Type RM Length L Ch R = 1 ,7628.432,204.389400,204.389400,204.389400
XS GIS Cut Line= 6
 991080.31166046758621.451500849990932.953760586758572.785582934
990827.241101114 758521.74585594 990629.20758667758359.797258707
990416.897959857758408.976585099990282.676614438758422.433003133
#Sta/Elev= 30
9557.63199.140329584.06798.870149636.288100.09929721.56499.556989732.48297.14717
 9787.6698.722929798.965100.48319810.26998.622969821.57497.736129868.45496.87436
9922.39897.729999944.07596.889579966.31685.938689973.30283.317099987.06375.40114
10000.7971.6512110014.6676.2020110028.5484.6691410057.5987.9761310070.1788.75621
10081.4489.1742210105.9788.52472 10143.189.6812710174.5191.3864810226.8796.59432
10237.3496.8897410288.7195.7930410309.1696.34292 10369.794.6174110442.2295.19172
#Mann= 3 , 0 , 0
9557.631    0.12       09557.631    0.12       010442.22    0.12       0
#XS Ineff= 2 , 0
       0                               0
Bank Sta=9557.631,10442.22
Exp/Cntr=0.3,0.1

Type RM Length L Ch R = 1 ,7424.043,362.455300,362.455300,362.455300
XS GIS Cut Line= 2
 990952.24015826758133.171140924990619.174589813758351.177694783
#Sta/Elev= 30
9799.63987.933249844.14788.512619856.09986.883239868.05187.231019880.00286.85077
9891.95487.163559894.27686.861579903.906 85.05569915.85782.498849927.80981.07505
9939.76180.395719949.05579.637659963.66478.061339975.616 74.96849985.57471.17485
9987.56870.638149999.51968.9477310011.4772.4614210022.09 74.014910023.4274.16377
10040.3574.2528510047.33 74.703510076.8779.3450810095.13 82.447510130.9982.93692
10149.9183.8310810166.8485.3180210178.7986.1144810190.7587.2429310197.7187.65365
#Mann= 3 , 0 , 0
9799.639    0.12       09799.639    0.12       010197.71    0.12       0
#XS Ineff= 2 , 0
       0                               0
Bank Sta=9799.639,10197.71
Exp/Cntr=0.3,0.1

Type RM Length L Ch R = 1 ,7061.587,289.741000,289.741000,289.741000
XS GIS Cut Line= 2
990594.783021063 758088.00806728990370.824687749758288.528900638
#Sta/Elev= 28
9821.18788.685079831.66988.489859847.74187.531789874.58682.596869888.009 81.2651
9901.43180.755389928.27680.574169936.60980.259159941.69979.80612  9951.678.65326
9955.12278.406819966.59276.585629981.58370.342989996.57566.6488110008.8165.35096
10011.5766.3010210022.2374.1602310026.5677.8830210035.6683.6601310041.5585.61767
10049.0887.2761810056.5488.53967 10062.589.2818410075.92 90.459510089.3591.32548
10101.5191.1967110116.1991.29271 10121.891.46052
#Mann= 3 , 0 , 0
9821.187  0.0605       09821.187  0.0605       0 10121.8  0.0605       0
#XS Ineff= 2 , 0
       0                               0
Bank Sta=9821.187,10121.8
Exp/Cntr=0.3,0.1

Type RM Length L Ch R = 1 ,6771.846,199.890500,199.890500,199.890500
XS GIS Cut Line= 2
990607.803854376 757931.75806728990269.262187719 758002.07056728
#Sta/Elev= 30
9861.20284.668029864.066 84.81499874.27984.427049894.70682.88368 9904.9281.64075
9915.13379.410319925.34777.91118 9935.5677.457759945.77376.206779955.98773.32928
  9966.269.747369976.41466.880019986.627 65.6226 9996.8463.3380810007.0563.45266
10017.2764.1533410037.69 70.520610047.9172.4504810058.1273.5574310068.3374.02775
10078.5574.9485410088.7676.6816510098.9778.9496210123.0282.8378310129.6183.37101
10139.8383.5614710160.2583.1933710170.47 83.414110201.1185.5776610206.9786.36241
#Mann= 3 , 0 , 0
9861.202    0.12       09861.202    0.12       010206.97    0.12       0
#XS Ineff= 2 , 0
       0                               0
Bank Sta=9861.202,10206.97
Exp/Cntr=0.3,0.1

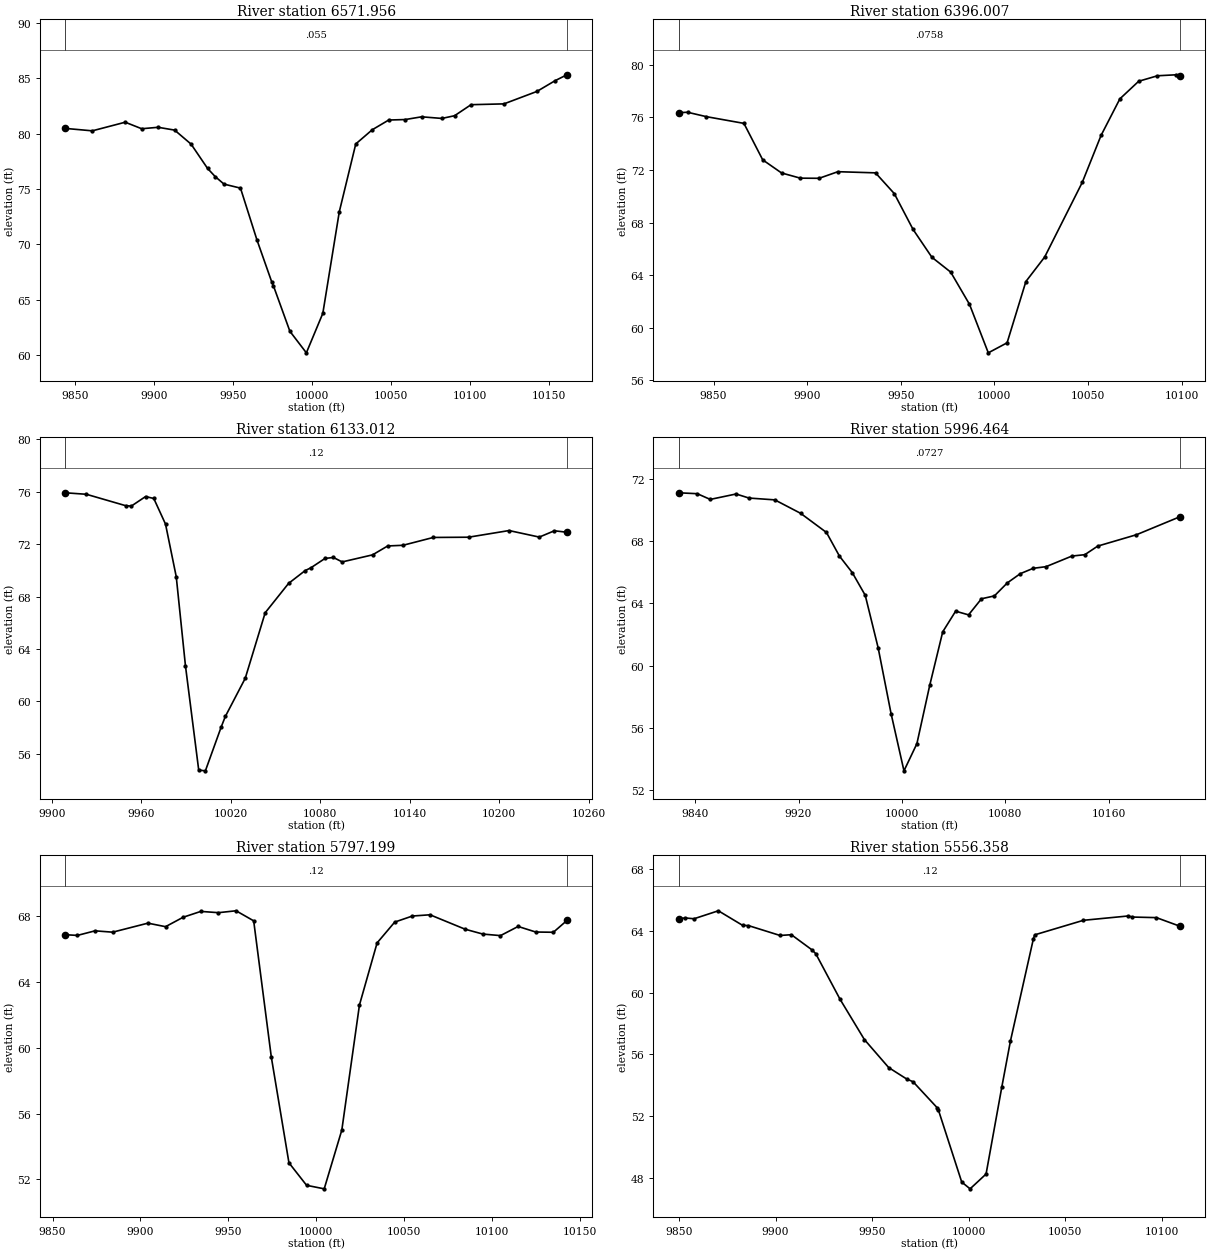
Type RM Length L Ch R = 1 ,6571.956,175.948800,175.948800,175.948800
XS GIS Cut Line= 2
990511.449687749757788.528900623990206.762187719757877.070567295
#Sta/Elev= 30
 9844.0380.471989861.16180.250939881.98881.029399892.40280.440779902.81580.57037
9913.22980.316979923.64379.049219934.05676.85567 9938.8976.11728 9944.4775.43577
9954.884 75.07489965.29770.391899974.72666.563899975.71166.251129986.125 62.1394
9996.53860.1919710006.9563.7621810017.3772.9432310027.7879.0662610038.1980.34629
10048.6181.2274110059.0281.2709110069.4381.5177210082.2381.3720710090.2681.61613
10100.6882.61307 10121.582.6868710142.3383.81091 10153.984.7885910161.3285.31596
#Mann= 3 , 0 , 0
 9844.03   0.055       0 9844.03   0.055       010161.32   0.055       0
#XS Ineff= 2 , 0
       0                               0
Bank Sta=9844.03,10161.32
Exp/Cntr=0.3,0.1

Type RM Length L Ch R = 1 ,6396.007,262.995300,262.995300,262.995300
XS GIS Cut Line= 2
990479.765659958757650.942095071990212.838576645757674.813622862
#Sta/Elev= 26
9831.33476.367389836.11976.398689846.15976.064419866.23975.551959876.27972.77511
9886.31871.779559896.35871.382049906.39871.372229916.43871.874429936.51871.78606
9946.55870.206229956.59867.475079966.63865.360249976.67864.231129986.71861.78017
9996.75858.08644 10006.858.8492210016.8463.5150110026.8865.3803110046.9671.06369
   1005774.6381210067.0477.4193710077.0878.7569710087.1279.1760110097.1679.25139
10099.3379.17935
#Mann= 3 , 0 , 0
9831.334  0.0758       09831.334  0.0758       010099.33  0.0758       0
#XS Ineff= 2 , 0
       0                               0
Bank Sta=9831.334,10099.33
Exp/Cntr=0.3,0.1

Type RM Length L Ch R = 1 ,6133.012,136.548000,136.548000,136.548000
XS GIS Cut Line= 4
990525.338576645757644.431678414 990390.78996554757525.074039519
990301.814271092757507.712928399990236.710104406757518.563622847
#Sta/Elev= 30
 9908.86 75.92149923.07275.806879949.41574.93715 9953.2174.905759962.78375.63421
9968.27975.485439976.15173.532119983.348 69.51619989.51862.720549998.41754.76212
10002.8954.7049710013.4958.0499810016.2558.8512610029.6261.7676610042.9966.76802
10058.6969.0076410069.7269.9774910073.7670.2064110083.0970.9084610088.7270.98762
10094.62 70.6454   1011571.1842210125.1871.8646310135.3771.9136610155.7572.51254
10179.3772.5312910206.5673.0390610226.8372.5405810236.9773.0218110245.3872.90952
#Mann= 3 , 0 , 0
 9908.86    0.12       0 9908.86    0.12       010245.38    0.12       0
#XS Ineff= 2 , 0
       0                               0
Bank Sta=9908.86,10245.38
Exp/Cntr=0.3,0.1

Type RM Length L Ch R = 1 ,5996.464,199.264900,199.264900,199.264900
XS GIS Cut Line= 2
990629.505243301757459.969872862990241.050382197757462.140011728
#Sta/Elev= 30
9827.14671.094579841.65171.035129851.65270.668849871.65271.016459881.65270.75668
9901.65270.639559921.65369.775589941.65368.547669951.653 67.03699961.65365.96783
9971.65364.517959981.65461.149339991.65456.9286310001.6553.2524110011.6554.99366
10021.6558.7604410031.6562.1715410041.6563.4973810051.6563.2602410061.6564.29315
10071.6664.4773110081.6665.3118910091.6665.9014710101.6666.2469210111.6666.35363
10131.6667.0335510141.6667.1223610151.6667.6730410181.6668.4029610215.6169.56731
#Mann= 3 , 0 , 0
9827.146  0.0727       09827.146  0.0727       010215.61  0.0727       0
#XS Ineff= 2 , 0
       0                               0
Bank Sta=9827.146,10215.61
Exp/Cntr=0.3,0.1

Type RM Length L Ch R = 1 ,5797.199,240.841300,240.841300,240.841300
XS GIS Cut Line= 2
990591.923770607757282.340007052990307.304103017757258.117056608
#Sta/Elev= 28
9857.18466.890739864.13266.847549874.16967.125869884.20567.044319904.27767.59282
9914.31367.378499924.34967.953029934.385 68.30759944.42268.230539954.45868.34591
9964.49467.73397 9974.5359.445729984.56653.014629994.60251.6456610004.6451.43083
10014.6755.0073310024.71  62.61710034.7566.3915310044.7867.6574810054.8268.02639
10064.8668.1023810084.9367.2221310094.9666.92897   1010566.8353110115.04 67.3919
10125.0767.0536110135.1167.0389310142.8367.75595
#Mann= 3 , 0 , 0
9857.184    0.12       09857.184    0.12       010142.83    0.12       0
#XS Ineff= 2 , 0
       0                               0
Bank Sta=9857.184,10142.83
Exp/Cntr=0.3,0.1

Type RM Length L Ch R = 1 ,5556.358,340.169000,340.169000,340.169000
XS GIS Cut Line= 2
 990547.03996554757171.341400638990388.619826615756965.178206176
#Sta/Elev= 29
9849.73464.779429853.08264.835479857.73164.781919870.34365.298999882.95464.35228
9885.90664.340869902.31863.699969908.17763.75007 9918.7362.780349920.78862.52778
  9933.4 59.57039946.01156.961519958.62255.144989967.96654.403499971.23454.22938
9983.84552.530419984.379 52.39569996.45747.7332310000.7947.2940610009.0748.25271
 10017.253.8690910021.6856.8561510033.6163.4946110034.2963.7411910059.5164.68227
10082.8564.9645410084.74 64.893210097.3564.8553510109.7364.28832
#Mann= 3 , 0 , 0
9849.734    0.12       09849.734    0.12       010109.73    0.12       0
#XS Ineff= 2 , 0
       0                               0
Bank Sta=9849.734,10109.73
Exp/Cntr=0.3,0.1

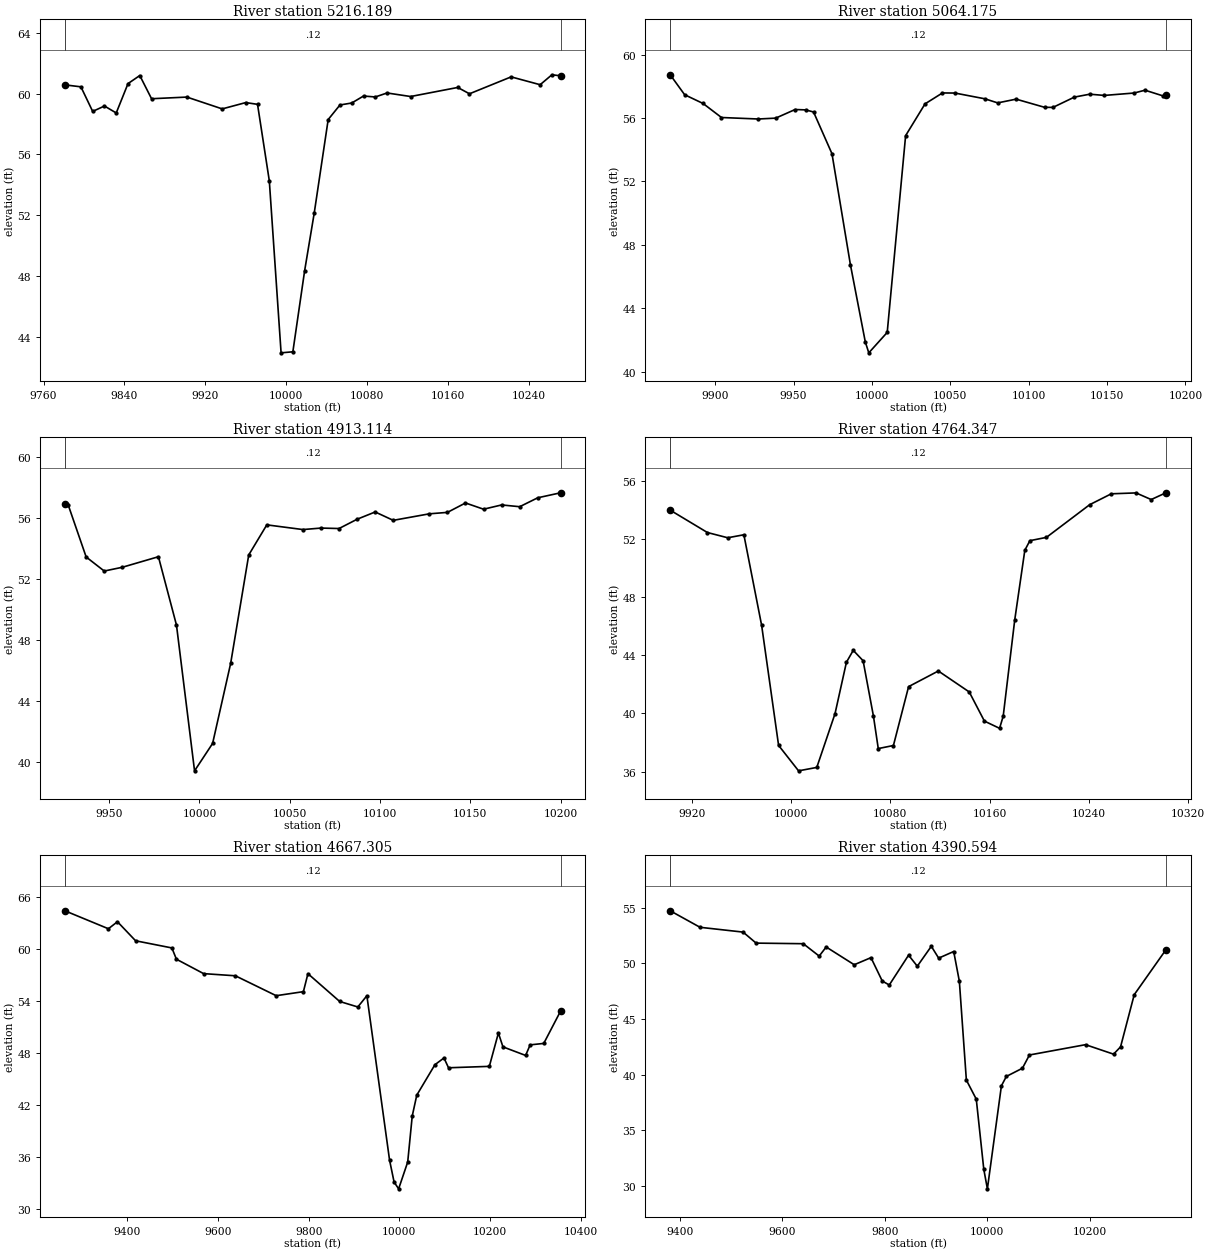
Type RM Length L Ch R = 1 ,5216.189,152.013700,152.013700,152.013700
XS GIS Cut Line= 2
 990898.60246554757021.601817295990477.595521092756769.865706176
#Sta/Elev= 30
9781.08360.582679796.93160.453769808.583 58.83519820.23459.191149831.88558.73331
9843.53760.665829855.18861.197189866.83959.670259901.79359.779189936.747 59.0014
 9960.0559.416729971.701 59.30149983.35254.269849995.00442.9462310006.6543.01465
10018.3148.3526810027.7852.1378210041.6158.3020510053.2659.2591110064.9159.38945
10076.5659.8474510088.2159.7869310099.8760.0494810123.1759.8157910169.77 60.4122
10181.4259.9958810222.6361.1087610251.3360.5928510262.9861.2467410271.6161.17871
#Mann= 3 , 0 , 0
9781.083    0.12       09781.083    0.12       010271.61    0.12       0
#XS Ineff= 2 , 0
       0                               0
Bank Sta=9781.083,10271.61
Exp/Cntr=0.3,0.1

Type RM Length L Ch R = 1 ,5064.175,151.060400,151.060400,151.060400
XS GIS Cut Line= 2
990902.858115554756850.326630726990633.642970711756684.354187042
#Sta/Elev= 30
 9871.2558.729839880.48157.471479892.22956.919659903.97756.035279927.47255.94093
9938.56655.996019950.96756.539829957.62156.515769962.71556.383599974.463 53.7532
 9986.2146.763949995.73241.881929997.958 41.195310009.7142.4838110021.45 54.8912
10033.8456.8957210044.9557.58419 10052.957.5778810071.9557.2160510080.1956.95707
10091.9457.1932210110.0656.6793310115.4356.6722310129.1257.3222210138.9357.50574
10148.1757.4276610167.2357.5793110174.1757.7579610185.9257.3901310187.5257.47371
#Mann= 3 , 0 , 0
 9871.25    0.12       0 9871.25    0.12       010187.52    0.12       0
#XS Ineff= 2 , 0
       0                               0
Bank Sta=9871.25,10187.52
Exp/Cntr=0.3,0.1

Type RM Length L Ch R = 1 ,4913.114,148.767700,148.767700,148.767700
XS GIS Cut Line= 2
990906.778724462756646.454967618990632.336101055756643.841228366
#Sta/Elev= 26
9925.52256.86647  9927.3 56.85499937.30153.424329947.30152.503249957.30252.75042
9977.30353.441969987.303 48.95899997.30439.40698 10007.341.20193 10017.346.45252
 10027.353.5569710037.3155.5306410057.3155.2220410067.3155.3199110077.3155.29027
10087.3155.8991610097.3156.3753510107.3155.8264410127.3156.2543810137.3156.34836
10147.31 56.965310157.3156.5565310167.3156.8361310177.3156.7202310187.3157.30521
10199.9857.63326
#Mann= 3 , 0 , 0
9925.522    0.12       09925.522    0.12       010199.98    0.12       0
#XS Ineff= 2 , 0
       0                               0
Bank Sta=9925.522,10199.98
Exp/Cntr=0.3,0.1

Type RM Length L Ch R = 1 ,4764.347,97.042300,97.042300,97.042300
XS GIS Cut Line= 3
990898.937506616756565.429050252990786.546718031756460.879479423
990585.288794219756319.737558842
#Sta/Elev= 30
9902.67454.008039932.66852.465639949.025 52.10529962.03252.31085 9976.3446.06749
9989.99837.7990810006.0836.0460110020.7636.2817710035.4439.9816610044.6343.52749
10050.12 44.347810058.0643.6331610066.41 39.809910070.2837.5807210082.49 37.7914
10094.71 41.847810118.66 42.925110143.5641.4808710155.7839.4728610167.9938.97561
10170.9139.80797 10180.246.4411810188.3351.2434610192.4251.9045410205.7452.13228
10240.5854.3837410257.9955.1340610277.9255.1953710290.1354.7374910301.9955.20454
#Mann= 3 , 0 , 0
9902.674    0.12       09902.674    0.12       010301.99    0.12       0
#XS Ineff= 2 , 0
       0                 10050.9       0
Bank Sta=9902.674,10301.99
Exp/Cntr=0.3,0.1

Type RM Length L Ch R = 1 ,4667.305,276.710900,276.710900,276.710900
XS GIS Cut Line= 2
990934.282966703757190.922340155990902.131524444756097.773301706
#Sta/Elev= 30
9262.23864.393699358.20262.324139378.21163.131139418.22860.937629498.26260.11371
9508.26758.815549568.29357.155079638.32356.905959728.36254.612659788.38855.07846
9798.39257.148969868.42253.94873 9908.4453.313979928.44854.60849 9978.4735.67323
9988.47433.144519998.47932.3666910018.49 35.454610028.4940.75442 10038.543.15725
10078.5146.6632110098.52 47.441210108.5346.3109310198.5746.4728910218.5750.31529
10228.5848.71977 10278.647.73164 10288.648.9489910318.62 49.116110355.8652.85137
#Mann= 3 , 0 , 0
9262.238    0.12       09262.238    0.12       010355.86    0.12       0
#XS Ineff= 2 , 0
       0                               0
Bank Sta=9262.238,10355.86
Exp/Cntr=0.3,0.1

Type RM Length L Ch R = 1 ,4390.594,493.988900,493.988900,493.988900
XS GIS Cut Line= 2
991571.953239113 756767.59501645990912.848671824756060.263285682
#Sta/Elev= 30
9381.68954.73604 9439.9153.249719523.90652.817269549.25851.826569641.25651.77274
9672.27550.660179685.94451.477969740.61849.881379773.27450.518739795.29248.41619
 9808.9648.057849846.61750.740679863.63449.750699890.97151.540179905.29250.47457
9934.62951.071999945.64648.393189959.31439.503199978.63537.787129993.30431.47395
10000.3229.7168910027.6638.9866710037.3139.8307910068.6640.5693610082.3341.76096
10191.6842.6883110246.3541.8355410260.02 42.490510286.6847.1853510348.5151.23054
#Mann= 3 , 0 , 0
9381.689    0.12       09381.689    0.12       010348.51    0.12       0
#XS Ineff= 2 , 0
       0                               0
Bank Sta=9381.689,10348.51
Exp/Cntr=0.3,0.1

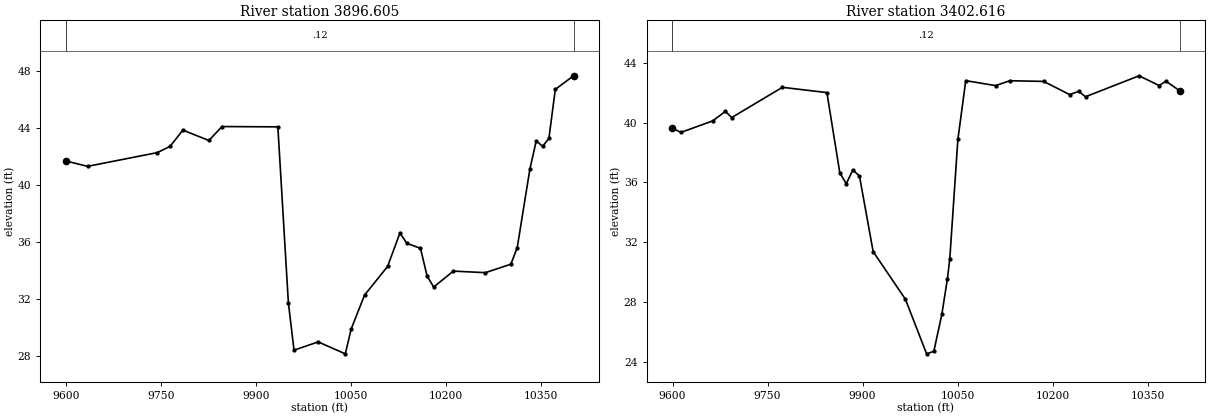
Type RM Length L Ch R = 1 ,3896.605,493.988900,493.988900,493.988900
XS GIS Cut Line= 6
991719.700532389755816.105555871991480.955724874755835.834419109
991395.922904755755874.541578765991219.337769289756004.831165912
991103.414736498756029.147974875990976.321032023756026.921373721
#Sta/Elev= 30
9599.18541.702459633.90541.316859744.06942.28001 9764.2442.722379784.41143.85836
9825.393 43.12949846.18944.106999934.26544.086239950.83131.76392 9959.7528.42934
 9997.8929.0104610040.6428.1729110050.0329.9236510071.0432.2906110107.3834.29743
10126.9136.6470910137.7935.9207810159.3335.5678610169.7333.6304710180.1332.85553
10211.1833.9727910261.7733.8639710301.9334.4576510311.9435.6143910331.9641.13049
10341.9743.1055310351.97 42.723210361.9843.2809610372.0246.7107810400.8347.66675
#Mann= 3 , 0 , 0
9599.185    0.12       09599.185    0.12       010400.83    0.12       0
#XS Ineff= 2 , 0
       0                               0
Bank Sta=9599.185,10400.83
Exp/Cntr=0.3,0.1

Type RM Length L Ch R = 1 ,3402.616,0.000000,0.000000,0.000000
XS GIS Cut Line= 6
991609.283558865 755635.43756942991411.149615823755634.341313153
991315.998948721755618.586770163991261.424073845  755592.7477102
 991107.65744764755488.554053762990864.001048157755397.391300597
#Sta/Elev= 30
9599.10539.632439613.38839.349199663.38840.117969683.38840.755069693.38840.34123
9773.39842.364099843.624 42.01199863.97636.642889874.20935.91335  9884.636.83356
9895.03336.425989916.62331.369979967.49428.1840210001.0124.52824 10012.424.69807
   1002527.16381 10033.929.56405 10037.630.9075210050.3438.8755710062.7942.81177
10109.78 42.478610132.3442.8052510185.6742.7608510226.57 41.882210241.1442.09304
10251.7841.7338610336.4143.1369310368.1442.4798710378.7242.7740310400.9442.11837
#Mann= 3 , 0 , 0
9599.105    0.12       09599.105    0.12       010400.94    0.12       0
#XS Ineff= 2 , 0
       0                               0
Bank Sta=9599.105,10400.94
Exp/Cntr=0.3,0.1